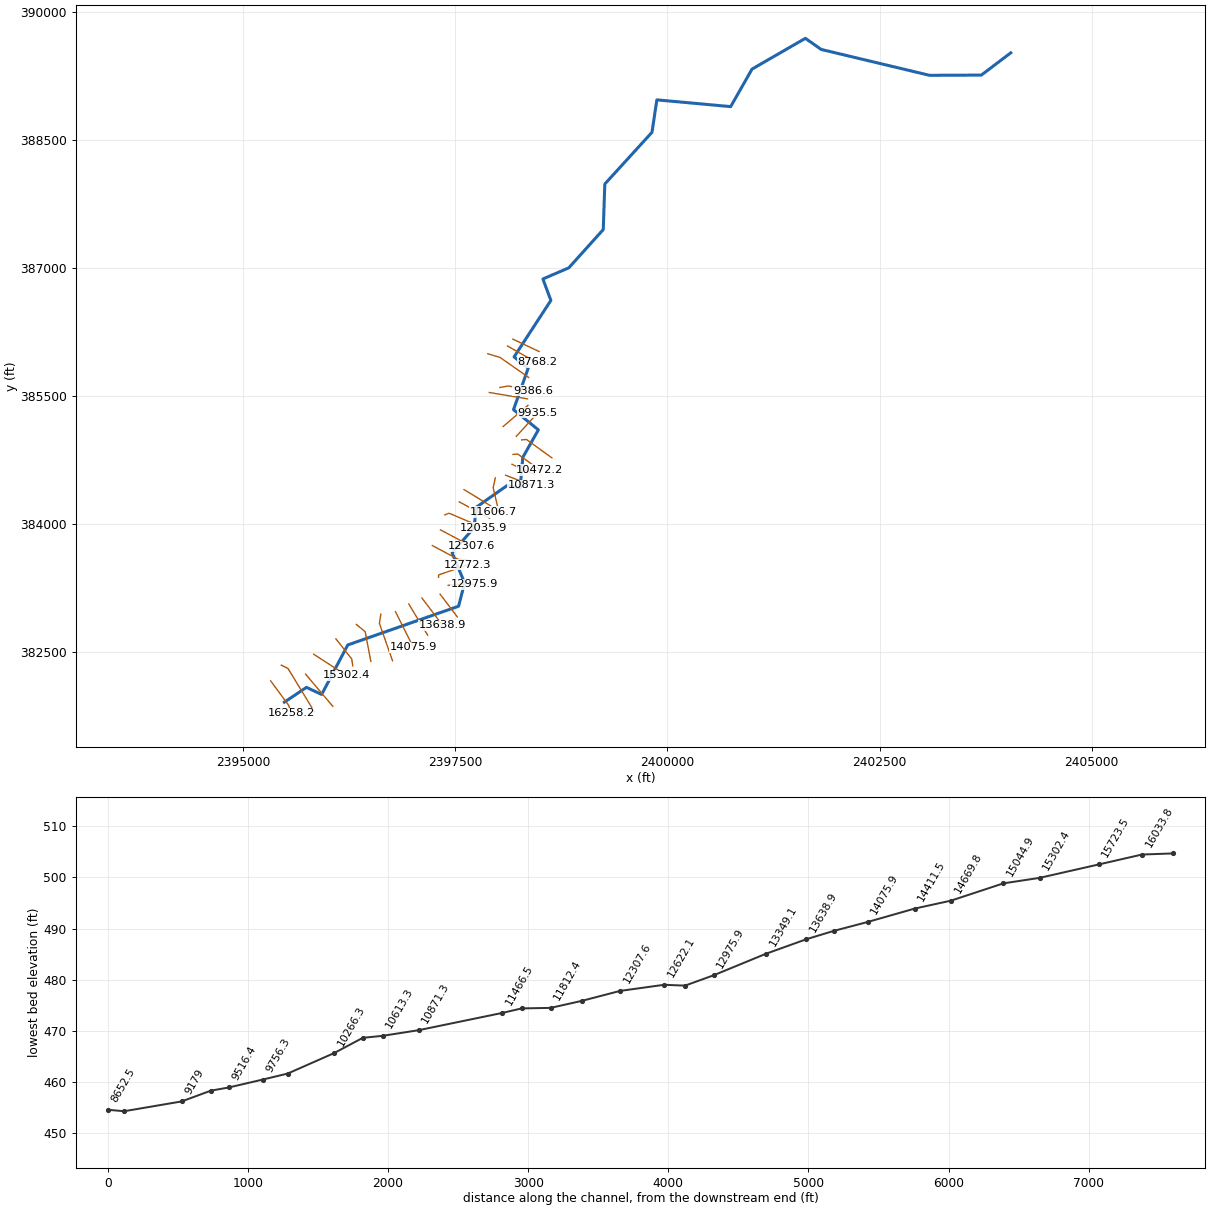
--- TULLISBRRN.prj (project) ---

Proj Title=TULLISBRRN
Current Plan=p01
Default Exp/Contr=0,0
English Units
Geom File=g01
Flow File=f01
Plan File=p01
BEGIN DESCRIPTION:
END DESCRIPTION:
DSS Export Rating Curves= 0
DSS Export Rating Curve Sorted= 0
DSS Export Volume Flow Curves= 0
DXF OffsetX= 0
DXF OffsetY= 0
DXF ScaleX= 0
DXF ScaleY= 0

--- TULLISBRRN.p01 (plan) ---

Plan Title=Floodplain
Program Version=4.00
Geom File=g01
Flow File=f01
K Sum by GR=0
Std Step Tol=0.01
Critical Tol=0.01
Num of Std Step Trials=20
Max Error Tol=0.3
Flow Tol Ratio=0.001
Split Flow NTrial=30
Split Flow Tol=0.02
Split Flow Ratio=0.02
Log Output Level=0
Friction Slope Method=1
Unsteady Friction Slope Method=2
Unsteady Bridges Friction Slope Method=1
Global Log Level=0
CheckData=False
Run HTab=0
Run UNet=0
Run PostProcess=0
UNET Theta=0
UNET Theta Warmup=0
UNET ZTol=0
UNET ZSATol=0
UNET MxIter=0
UNET MaxInSteps=0
UNET DtIC=0
UNET DtMin=0
UNET MaxCRTS=0
UNET WFStab=0
UNET SFStab=0
UNET WFX=0
UNET SFX=0
UNET DSS MLevel=0
UNET DZMax Abort=0
UNET Convert EG Bridges=0
UNET Use Existing IB Tables=0
UNET Froude Limit=0
UNET Froude Power=0
Write IC File=0
Echo Input=False
Echo Output=False
Write Detailed=0

--- TULLISBRRN.f01 (steady flow) ---

Flow Title=NFF Regression Equation
Program Version=4.00
Number of Profiles=1
Profile Names=P100yr
River Rch & RM=TULLISBRRN,Main      ,16258.2
523.4832
River Rch & RM=TULLISBRRN,Main      ,16033.8
523.9992
River Rch & RM=TULLISBRRN,Main      ,15723.5
606.8619
River Rch & RM=TULLISBRRN,Main      ,13349.1
629.1049
River Rch & RM=TULLISBRRN,Main      ,12035.9
698.5030
River Rch & RM=TULLISBRRN,Main      ,8652.5
740.7959
River Rch & RM=TULLISBRRN,Main      ,7560.2
875.2930
River Rch & RM=TULLISBRRN,Main      ,5065.5
907.9039
River Rch & RM=TULLISBRRN,Main      ,4612
1047.938
River Rch & RM=TULLISBRRN,Main      ,3062.2
1073.270
River Rch & RM=TULLISBRRN,Main      ,456.4
1189.799
River Rch & RM=TULLISBRRN,Main      ,242.2
1190.323
Boundary for River Rch & Prof#=TULLISBRRN,Main      ,1
Up Type=0
Dn Type=3
Dn Slope=0.005703

--- TULLISBRRN.g01 (geometry) ---

Geom Title=USGS 10m DEM
Program Version=5.03

River Reach=TULLISBRRN      ,Main
Reach XY= 30
     2395486.788      381908.014     2395747.205      382081.625
     2395926.024      381998.291     2396233.576      382578.673
     2397539.566        383033.1     2397609.879      383306.538
     2397462.743      383660.704     2397720.555      383952.371
     2397750.504      384195.861     2398109.879      384447.163
     2398264.826      384419.819     2398296.076      384779.194
      2398479.67      385100.809     2398186.701      385337.788
     2398359.878      385824.767     2398193.212      385956.278
     2398626.806      386619.038     2398533.055       386870.34
     2398837.743      387000.548     2399243.993      387449.767
     2399262.222      387983.621     2399818.212      388590.392
     2399875.503        388970.6     2400745.295      388891.173
     2400996.597      389331.277     2401625.503      389691.955
     2401811.701      389561.746     2403087.743      389258.361
      2403698.42      389260.965     2404044.902      389521.841

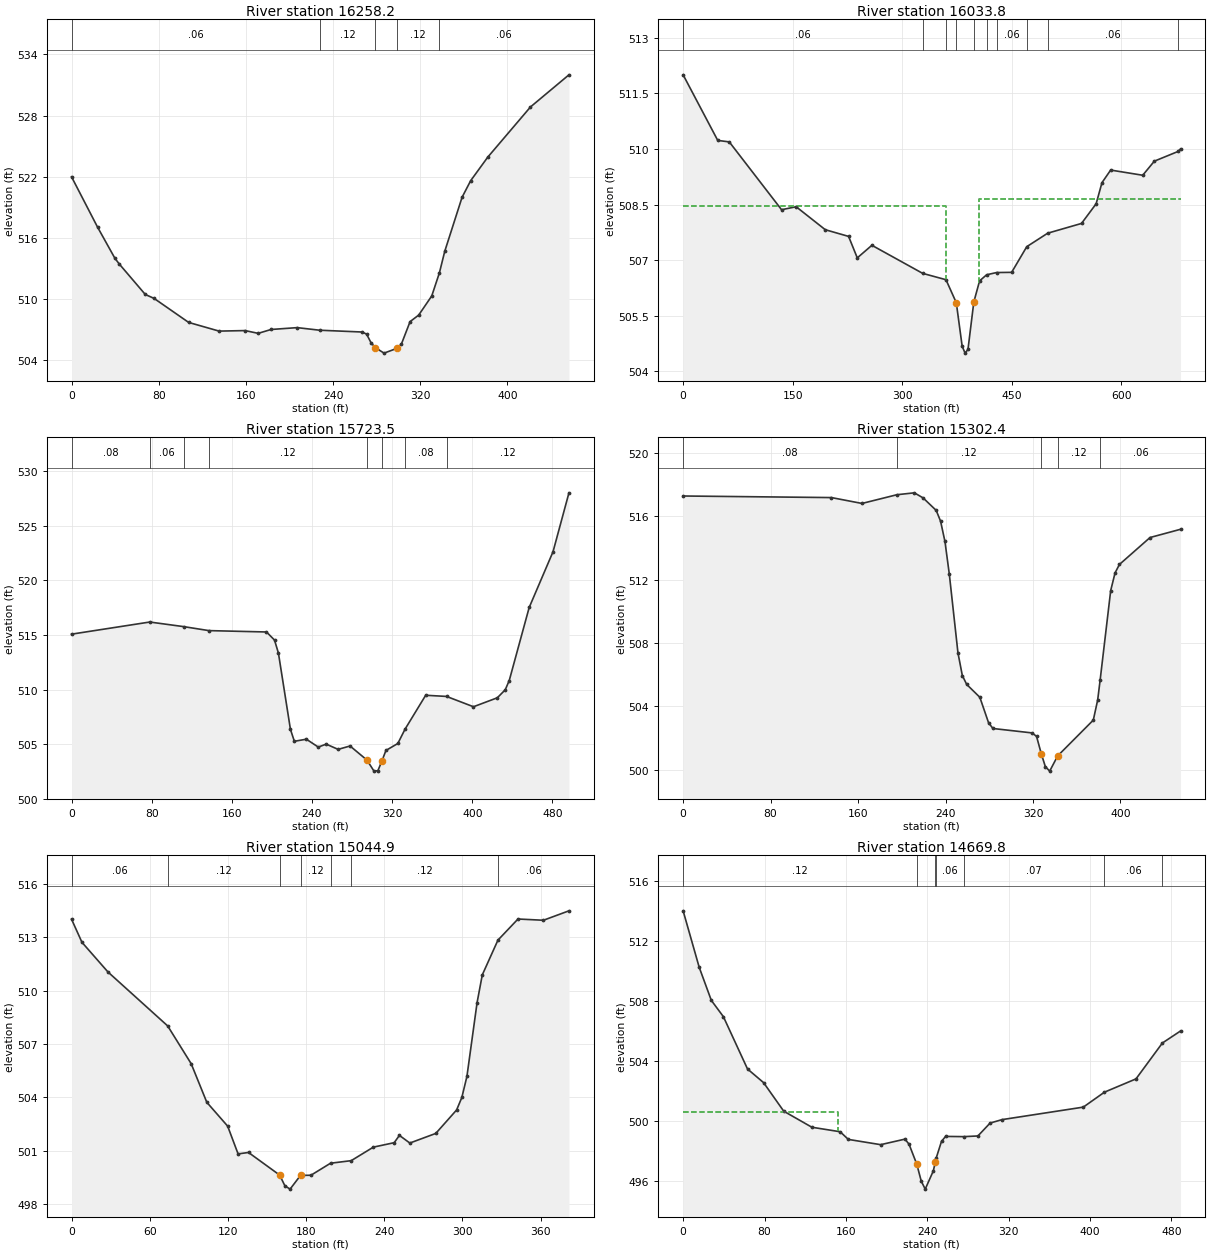
Type RM Length L Ch R = 1 ,16258.2 ,226.3,224.3,222.3
XS GIS Cut Line= 3
     2395324.509      382158.339     2395537.926      381870.349
     2395566.428      381776.537
#Sta/Elev= 30
       0     522    23.9  517.06    39.8  514.01    43.8  513.45    67.7  510.46
    75.7  510.08   107.5  507.72   135.4  506.87   159.3  506.92   171.3  506.65
   183.2  507.03   207.1  507.21  227.76506.9557   266.8  506.78   270.8  506.57
   274.8  505.74   278.8  505.25   286.8  504.71   298.7  505.18   302.7  505.59
   310.7   507.8   318.6  508.44   330.6  510.32  337.62512.5864   342.5  514.69
   358.4  519.99   366.3  521.62     382  523.93   421.2  528.85   456.5     532
#Mann= 5 ,-1 , 0
       0     .06       0  227.76     .12       0   278.8    .045       0
   298.7     .12       0  337.62     .06       0
Bank Sta=278.8,298.7
XS Rating Curve= 0 ,0
Exp/Cntr=0.3,0.1

Type RM Length L Ch R = 1 ,16033.8 ,307,310.4,307.7
XS GIS Cut Line= 3
     2395450.554      382342.098     2395528.661      382303.841
     2395839.375      381797.276
#Sta/Elev= 30
       0     512    47.4  510.23    63.2  510.19   134.8  508.36   154.8  508.44
   194.7  507.82   226.6  507.64   238.5  507.06   258.5   507.4   328.1 506.642
  359.97 506.471   374.1  505.85   382.1  504.68   386.1  504.49   390.1  504.59
   398.1  505.87     406  506.44  415.65506.6041  429.28506.6646   449.9  506.67
  470.61507.3627  499.25507.7264   545.6  507.99   565.6  508.52   573.6  509.09
   585.5  509.43   629.4  509.29   645.3  509.67  677.81509.9322   681.2     510
#Mann= 10 ,-1 , 0
       0     .06       0   328.1     .12       0  359.97     .06       0
   374.1    .045       0   398.1     .06       0  415.65     .08       0
  429.28     .06       0  470.61     .08       0  499.25     .06       0
  677.81    .016       0
#XS Ineff= 2 , 0
          360.09  508.46   405.2          508.65
Permanent Ineff=
       F       F
Bank Sta=374.1,398.1
XS Rating Curve= 0 ,0
Exp/Cntr=0.3,0.1

Type RM Length L Ch R = 1 ,15723.5 ,406,421.1,423.7
XS GIS Cut Line= 2
     2395736.609      382236.727     2396058.195      381858.456
#Sta/Elev= 30
       0  515.07    78.1  516.18  111.76515.7614  137.17515.3946   194.6  515.27
   202.6  514.53   206.5  513.34   218.5  506.36   222.4  505.27   234.4  505.46
   246.3  504.74   254.2  505.01   266.1  504.53     278  504.84   294.9  503.55
   301.9  502.54   305.8  502.58   309.9  503.49   313.8  504.43   325.7  505.07
  332.89506.3789   353.5  509.48  374.33509.3737   401.2  508.43     425  509.25
   432.9  509.98   436.9  510.83   456.8  517.51   480.6  522.61   496.5     528
#Mann= 8 ,-1 , 0
       0     .08       0    78.1     .06       0  111.76     .08       0
  137.17     .12       0   294.9    .045       0   309.9     .12       0
  332.89     .08       0  374.33     .12       0
Bank Sta=294.9,309.9
XS Rating Curve= 0 ,0
Exp/Cntr=0.3,0.1

Type RM Length L Ch R = 1 ,15302.4 ,264.5,257.5,250.3
XS GIS Cut Line= 2
       2395831.6      382470.659     2396214.175      382224.358
#Sta/Elev= 30
       0  517.28   135.7  517.18   163.6  516.81  195.57517.3603   211.5  517.48
   219.5  517.16   231.5  516.37   235.5  515.69   239.5  514.41   243.5  512.34
   251.4  507.38   255.4  505.95   259.4  505.39   271.4  504.58   279.4  502.97
   283.4  502.61   319.3  502.33   323.3  502.11   327.6  501.02   331.3  500.21
   335.3  499.92   342.6  500.88   375.2  503.14   379.2  504.41  381.45505.6644
   391.1  511.31   395.1  512.43   399.1  512.96   427.1  514.66     455  515.18
#Mann= 5 ,-1 , 0
       0     .08       0  195.57     .12       0   327.6    .045       0
   342.6     .12       0  381.45     .06       0
Bank Sta=327.6,342.6
XS Rating Curve= 0 ,0
Exp/Cntr=0.3,0.1

Type RM Length L Ch R = 1 ,15044.9 ,332.3,375.1,364
XS GIS Cut Line= 3
     2396094.443      382650.209     2396280.045      382415.154
     2396292.746      382333.946
#Sta/Elev= 30
       0  514.02       8  512.72      28  511.05   73.78508.0214    91.8   505.9
   103.8  503.73   119.8  502.39   127.8  500.83   135.8  500.91   159.7  499.64
   163.7  499.04   167.7  498.85   175.7  499.62   183.7  499.63  198.75500.3058
  214.62  500.45   231.6  501.21   247.6  501.46   251.6  501.87   259.6  501.44
   279.5  501.98   295.5   503.3   299.5     504   303.4  505.18   311.2  509.33
   315.2  510.89   327.2512.8431   342.6  514.03   362.1  513.96   381.7  514.49
#Mann= 7 ,-1 , 0
       0     .06       0   73.78     .12       0   159.7    .045       0
   175.7     .12       0  198.75     .06       0  214.62     .12       0
   327.2     .06       0
Bank Sta=159.7,175.7
XS Rating Curve= 0 ,0
Exp/Cntr=0.3,0.1

Type RM Length L Ch R = 1 ,14669.8 ,253.6,258.3,260.6
XS GIS Cut Line= 3
     2396334.535      382818.901     2396439.029      382734.256
     2396505.587       382386.01
#Sta/Elev= 30
       0  513.99    15.8  510.23    27.7  508.03    39.6  506.94    63.3  503.46
    79.1  502.55    98.9  500.65   126.6  499.58   154.4  499.28   162.4  498.77
   194.2  498.42   218.1  498.79   222.1  498.45   229.7  497.12   234.1  495.99
     238  495.46     246  496.68  247.81  497.24  248.95497.5627     254  498.64
     258  498.97  275.95498.9549   289.8     499   301.8  499.86   313.7  500.09
   393.4  500.92   414.2 501.916   445.2   502.8  471.16505.1896     489  505.99
#Mann= 7 ,-1 , 0
       0     .12       0   229.7    .045       0  247.81     .12       0
  248.95     .06       0  275.95     .07       0   414.2     .06       0
  471.16     .12       0
#XS Ineff= 2 , 0
          152.22  500.57
Permanent Ineff=
       F       F
Bank Sta=229.7,247.81
XS Rating Curve= 0 ,0
Exp/Cntr=0.3,0.1

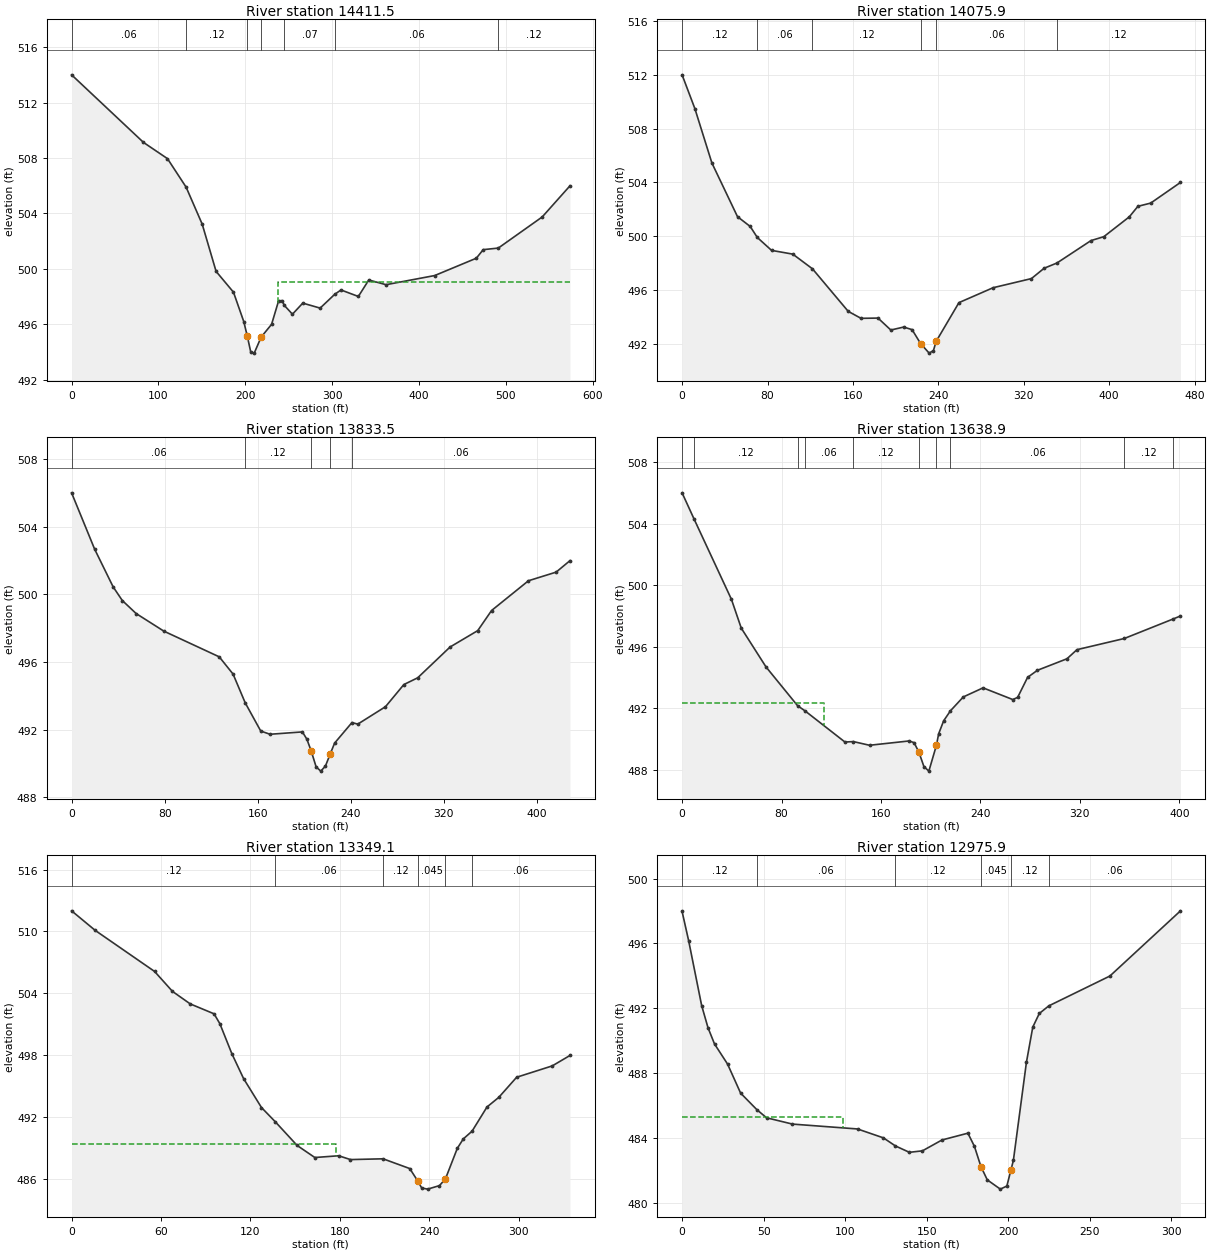
Type RM Length L Ch R = 1 ,14411.5 ,335.8,335.6,327
XS GIS Cut Line= 3
     2396623.481      382939.904     2396606.874      382830.707
     2396761.105      382393.723
#Sta/Elev= 30
       0     514    82.8  509.12   110.4  507.95  131.89  505.89   150.4  503.22
   166.4  499.81   186.4  498.31   198.3  496.18   202.3  495.14   206.3  493.99
   210.3  493.91   218.3  495.07   230.3  495.99   238.3  497.67   242.3   497.7
  245.04497.3506   254.3  496.72   266.2  497.52   286.2  497.16  302.95498.1525
   310.2  498.47   330.2     498   342.2  499.19   362.1  498.85   418.1  499.51
     466  500.76     474  501.38  491.34501.4936   541.9  503.74   573.9  505.99
#Mann= 7 ,-1 , 0
       0     .06       0  131.89     .12       0   202.3    .045       0
   218.3     .12       0  245.04     .07       0  302.95     .06       0
  491.34     .12       0
#XS Ineff= 2 , 0
                          237.76          499.06
Permanent Ineff=
       F       F
Bank Sta=202.3,218.3
XS Rating Curve= 0 ,0
Exp/Cntr=0.3,0.1

Type RM Length L Ch R = 1 ,14075.9 ,238.4,242.4,216.8
XS GIS Cut Line= 2
      2396795.73      382969.222      2397006.17      382552.537
#Sta/Elev= 30
       0  512.01      12  509.49    27.9  505.45    51.9  501.45    63.8  500.72
   70.46499.9006    83.8  498.94   103.7  498.66  122.12497.5664   155.6   494.4
   167.6  493.88   183.5   493.9   195.5  493.01   207.5  493.23   215.4  493.04
   223.4     492   231.4  491.29   235.4  491.48  237.99  492.17   259.3  495.05
   291.3  496.16   327.2  496.84   339.1  497.61  351.09497.9995     383  499.67
     395  499.96   418.9  501.44   426.9  502.22   438.9  502.46   466.8     504
#Mann= 6 ,-1 , 0
       0     .12       0   70.46     .06       0  122.12     .12       0
   223.4    .045       0  237.99     .06       0  351.09     .12       0
Bank Sta=223.4,237.99
XS Rating Curve= 0 ,0
Exp/Cntr=0.3,0.1

Type RM Length L Ch R = 1 ,13833.5 ,192.5,194.6,196.6
XS GIS Cut Line= 2
     2396952.114      383059.359     2397175.115      382693.536
#Sta/Elev= 30
       0     506    19.8  502.67    35.7  500.44    43.6  499.63    55.5  498.86
    79.3  497.82   126.9   496.3   138.8  495.28  149.26493.5764   162.6  491.91
   170.6  491.72   198.4  491.86   202.3  491.42     206  490.72   210.2  489.79
   214.2  489.54   218.2  489.84   222.2  490.54   226.1   491.2  240.99 492.412
     246  492.32   269.8  493.35   285.6  494.66   297.5  495.06   325.3  496.88
   349.1  497.85     361  499.04   392.7   500.8   416.5  501.31   428.4  501.99
#Mann= 5 ,-1 , 0
       0     .06       0  149.26     .12       0     206    .045       0
   222.2     .12       0  240.99     .06       0
Bank Sta=206,222.2
XS Rating Curve= 0 ,0
Exp/Cntr=0.3,0.1

Type RM Length L Ch R = 1 ,13638.9 ,258.1,289.8,286.6
XS GIS Cut Line= 2
     2397107.739      383128.913     2397350.663      382809.988
#Sta/Elev= 30
       0     506     9.5 504.322    39.7  499.08    47.6  497.21    67.5  494.69
   92.91492.1694   98.75491.8431     131  489.81  137.78489.8386   150.8   489.6
   182.6  489.88   186.6  489.77   190.5  489.15   194.5  488.22   198.5  487.92
  204.54  489.59   206.4  490.35   210.4  491.19  215.89491.8414   226.2  492.74
   242.1  493.33     266  492.57   269.9  492.71   277.9  494.01   285.8  494.47
   309.6  495.22   317.6  495.81  355.69496.5364  394.58497.7908   400.9     498
#Mann= 10 ,-1 , 0
       0     .08       0     9.5     .12       0   92.91    .016       0
   98.75     .06       0  137.78     .12       0   190.5    .045       0
  204.54     .12       0  215.89     .06       0  355.69     .12       0
  394.58     .06       0
#XS Ineff= 2 , 0
          114.04  492.35
Permanent Ineff=
       F       F
Bank Sta=190.5,204.54
XS Rating Curve= 0 ,0
Exp/Cntr=0.3,0.1

Type RM Length L Ch R = 1 ,13349.1 ,349.3,373.1,395.7
XS GIS Cut Line= 2
     2397321.773      383174.454     2397524.114      382908.205
#Sta/Elev= 30
       0     512    15.9   510.1    55.7  506.13    67.7   504.2    79.6  502.99
    95.6  502.03    99.5  501.07   107.5  498.18   115.4  495.76   127.4  492.96
  136.68491.5795   151.3  489.29   163.2  488.12   179.2  488.29   187.1  487.92
  208.99487.9951   226.9  487.05   232.2  485.86   234.9  485.17   238.9  485.06
   246.8   485.4   250.8  486.04   258.8  489.01   262.8  489.92   268.7  490.67
   278.7  493.01   286.6  493.94   298.6  495.89   322.5  496.99   334.4     498
#Mann= 6 ,-1 , 0
       0     .12       0  136.68     .06       0  208.99     .12       0
   232.2    .045       0   250.8     .12       0   268.7     .06       0
#XS Ineff= 2 , 0
          177.35  489.46
Permanent Ineff=
       F       F
Bank Sta=232.2,250.8
XS Rating Curve= 0 ,0
Exp/Cntr=0.3,0.1

Type RM Length L Ch R = 1 ,12975.9 ,198,203.6,208.7
XS GIS Cut Line= 3
     2397417.344      383277.767     2397639.282      383300.537
     2397721.099      383289.522
#Sta/Elev= 30
       0  497.97       4  496.18      12  492.17    15.9   490.8    19.9   489.8
    27.9  488.56    35.9  486.77   45.91485.7454    51.8  485.25    67.7  484.86
   107.6  484.56   123.5  484.01  130.82483.5142   139.4  483.12   147.4  483.21
   159.4  483.88   175.3   484.3   179.3  483.49   183.3  482.24   187.2  481.42
   195.2  480.85   199.2  481.04   201.7  482.03   203.2  482.62   211.2  488.67
   215.1  490.84   219.1  491.68  224.91492.1485   262.4  493.99   305.7  498.01
#Mann= 6 ,-1 , 0
       0     .12       0   45.91     .06       0  130.82     .12       0
   183.3    .045       0   201.7     .12       0  224.91     .06       0
#XS Ineff= 2 , 0
           98.61  485.27
Permanent Ineff=
       F       F
Bank Sta=183.3,201.7
XS Rating Curve= 0 ,0
Exp/Cntr=0.3,0.1

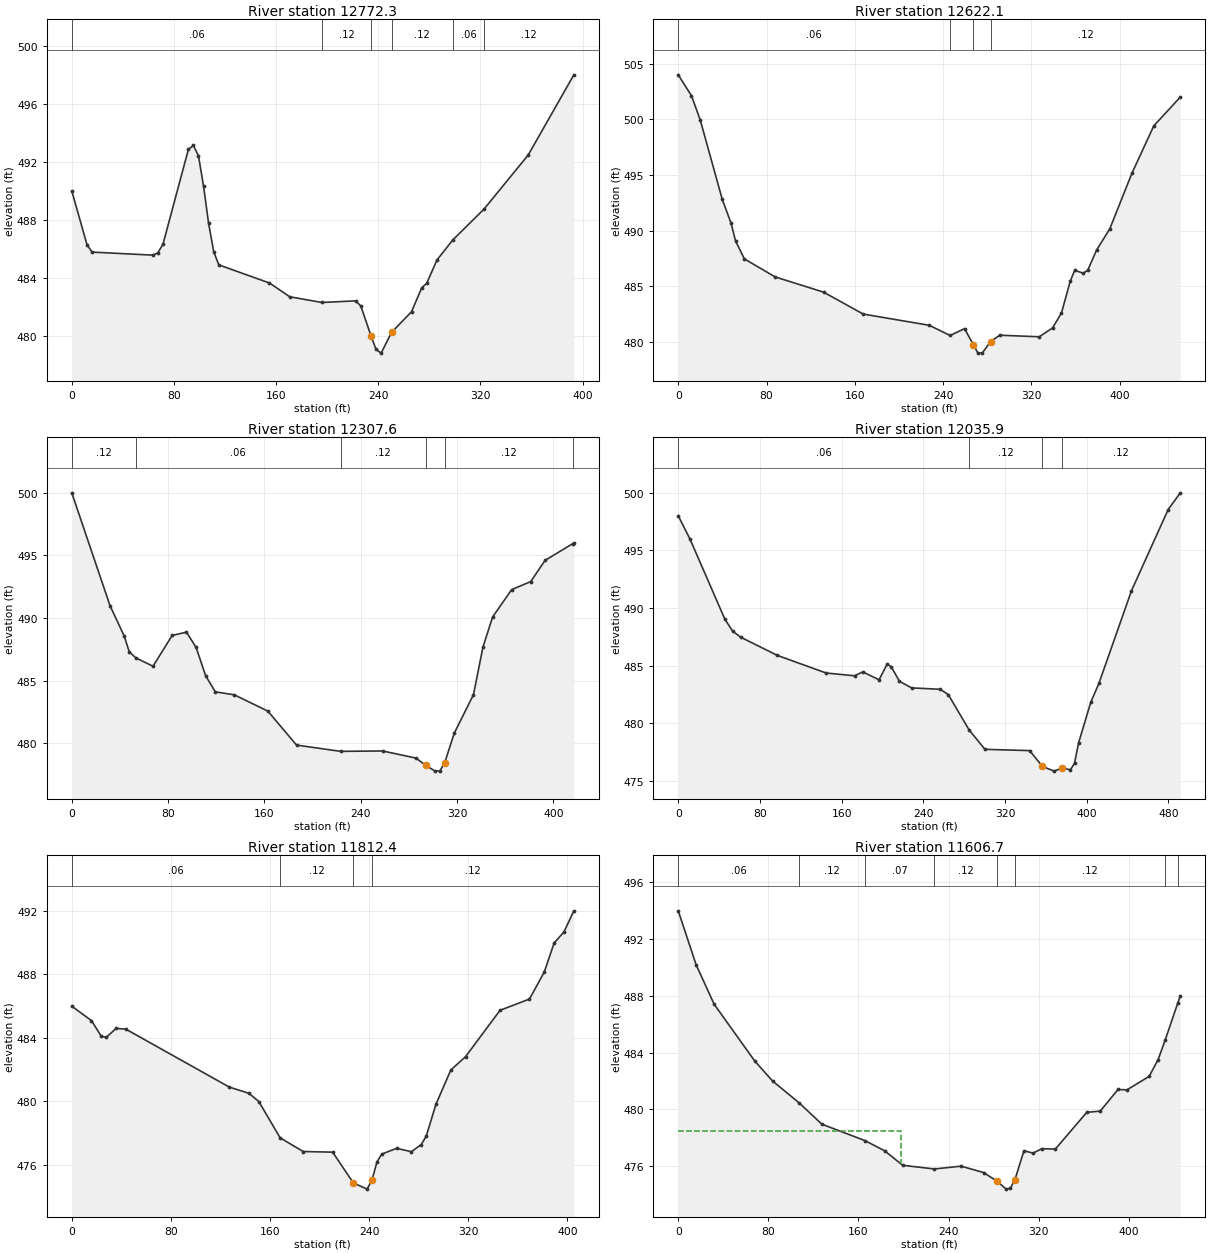
Type RM Length L Ch R = 1 ,12772.3 ,174.5,150.2,128.9
XS GIS Cut Line= 3
     2397303.147      383372.537     2397304.143      383400.229
     2397649.925      383518.348
#Sta/Elev= 30
       0     490    11.9  486.31    15.8  485.79    63.5  485.58    67.4  485.74
    71.4  486.33    91.3  492.86    95.2  493.14    99.2  492.42   103.2  490.32
   107.1  487.79   111.1  485.83   115.1  484.91   154.8  483.66   170.7  482.71
  195.81482.3202   222.3  482.43   226.3  482.08   234.2  480.04   238.2  479.09
   242.2  478.83   250.4  480.26     266  481.68     274  483.33   277.9  483.64
   285.9  485.24  298.29486.6231  322.77488.7512   357.4  492.48   393.1     498
#Mann= 6 ,-1 , 0
       0     .06       0  195.81     .12       0   234.2    .045       0
   250.4     .12       0  298.29     .06       0  322.77     .12       0
Bank Sta=234.2,250.4
XS Rating Curve= 0 ,0
Exp/Cntr=0.3,0.1

Type RM Length L Ch R = 1 ,12622.1 ,307.2,314.5,317
XS GIS Cut Line= 3
      2397229.76      383744.537     2397540.224      383580.428
     2397643.863      383576.789
#Sta/Elev= 30
       0     504      12  502.12      20  499.92    39.9   492.8    47.9  490.66
    51.9  489.08    59.9  487.46    87.8  485.84   131.7  484.47   167.6   482.5
   227.5  481.49  246.31480.5745   259.4  481.19   267.4  479.75   271.4  479.01
   275.4  478.99     283  480.03   291.3   480.6   327.2  480.46   339.2  481.26
   347.2  482.59   355.2  485.46   359.2  486.43   367.1  486.17   371.1  486.46
   379.1  488.26     391  490.16     411  495.14   430.9  499.42   454.9     502
#Mann= 4 ,-1 , 0
       0     .06       0  246.31     .12       0   267.4    .045       0
     283     .12       0
Bank Sta=267.4,283
XS Rating Curve= 0 ,0
Exp/Cntr=0.3,0.1

Type RM Length L Ch R = 1 ,12307.6 ,277.7,271.7,267
XS GIS Cut Line= 2
     2397325.317      383928.537     2397694.383      383734.269
#Sta/Elev= 30
       0     500    31.8  490.99    43.7  488.54    47.7  487.32    53.1486.8325
    67.5  486.16    83.4  488.62    95.3  488.88   103.3  487.66   111.2  485.41
   119.2  484.12     135  483.88   162.9  482.58   186.7  479.87  223.25479.3679
   258.2   479.4     286  478.83   293.9  478.26   301.9  477.79   305.8  477.81
   309.8  478.46   317.8  480.83   333.7  483.89   341.6  487.69   349.6  490.09
   365.4  492.27   381.3  492.92   393.2  494.61  416.27495.9485   417.1  495.99
#Mann= 6 ,-1 , 0
       0     .12       0    53.1     .06       0  223.25     .12       0
   293.9    .045       0   309.8     .12       0  416.27     .06       0
Bank Sta=293.9,309.8
XS Rating Curve= 0 ,0
Exp/Cntr=0.3,0.1

Type RM Length L Ch R = 1 ,12035.9 ,200.8,223.5,206.4
XS GIS Cut Line= 3
     2397377.427      384104.449     2397427.051      384123.473
     2397831.227      383953.425
#Sta/Elev= 30
       0     498    11.4     496    45.6  489.04    53.2     488    61.1  487.47
      97  485.89   144.8  484.36   172.7  484.12   180.7  484.46   196.6  483.77
   204.6  485.14   208.6   484.9   216.6  483.64   228.5  483.07   256.4  482.95
   264.4  482.49  284.82479.4265   300.3  477.74   344.1  477.63   356.6  476.26
   368.1  475.85     376  476.13     384  475.96     388  476.53     392   478.3
   403.9  481.82   411.9  483.46   443.8   491.5   479.7  498.54   491.6  499.99
#Mann= 4 ,-1 , 0
       0     .06       0  284.82     .12       0   356.6    .045       0
     376     .12       0
Bank Sta=356.6,376
XS Rating Curve= 0 ,0
Exp/Cntr=0.3,0.1

Type RM Length L Ch R = 1 ,11812.4 ,202.4,205.7,192.4
XS GIS Cut Line= 2
     2397547.452      384256.537      2397904.69      384065.113
#Sta/Elev= 30
       0     486    15.9  485.09    23.8  484.11    27.8  484.03    35.8   484.6
    43.7  484.55   127.2   480.9     143  480.51     151  479.99  168.22477.7009
   186.8  476.84   210.6   476.8   227.3  474.86   238.4  474.47   242.3  475.03
   246.4  476.19   250.3  476.68   262.2  477.04   274.2  476.83   282.1  477.28
   286.1   477.8     294  479.82     306  481.98   317.9  482.82   345.7  485.74
   369.5  486.45   381.4  488.15   389.4  489.98   397.4  490.69   405.3  492.01
#Mann= 4 ,-1 , 0
       0     .06       0  168.22     .12       0   227.3    .045       0
   242.3     .12       0
Bank Sta=227.3,242.3
XS Rating Curve= 0 ,0
Exp/Cntr=0.3,0.1

Type RM Length L Ch R = 1 ,11606.7 ,158.2,140.2,121.1
XS GIS Cut Line= 3
     2397604.114      384400.167     2397917.698      384210.121
     2397949.228      384137.651
#Sta/Elev= 30
       0     494    15.9  490.19    31.9  487.41    67.8  483.42    83.7     482
  107.28 480.458   127.5  478.95  165.72477.7944   183.3  477.07   199.3  476.05
  227.47475.7914   251.1  475.99     271  475.54     283  474.93     291  474.37
   294.9  474.44   298.9  475.04   306.9  477.08   314.9  476.91   322.8  477.22
   334.8   477.2   362.7  479.79   374.6  479.87   390.4   481.4   398.3  481.37
     418  482.32     426  483.51  432.31484.8947  443.61487.5338   445.7     488
#Mann= 8 ,-1 , 0
       0     .06       0  107.28     .12       0  165.72     .07       0
  227.47     .12       0     283    .045       0   298.9     .12       0
  432.31     .06       0  443.61     .12       0
#XS Ineff= 2 , 0
          197.63  478.45
Permanent Ineff=
       F       F
Bank Sta=283,298.9
XS Rating Curve= 0 ,0
Exp/Cntr=0.3,0.1

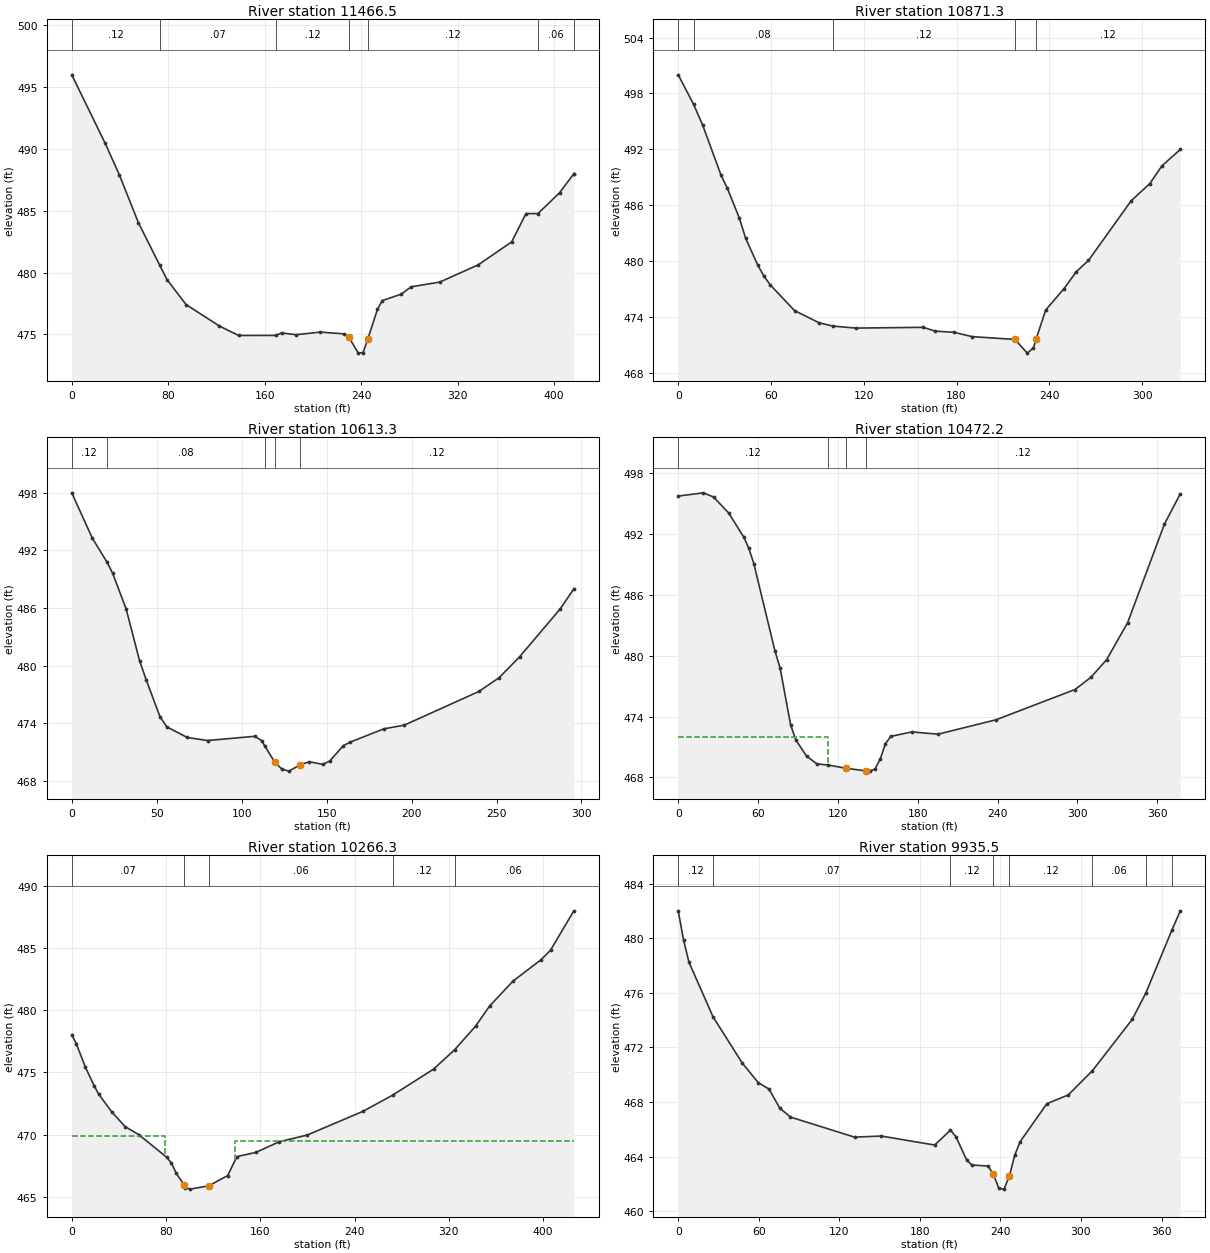
Type RM Length L Ch R = 1 ,11466.5 ,470.4,595.2,499.4
XS GIS Cut Line= 3
     2397972.114      384538.353     2397946.972      384422.513
      2398015.64      384132.537
#Sta/Elev= 30
       0     496    27.7  490.46    39.5   487.9    55.3  484.03   72.88480.6107
      79  479.43    94.8  477.41   122.5  475.67   138.4  474.91  169.36474.9132
   174.2  475.11   186.1  474.97     206  475.18   225.8  475.04     230  474.75
   237.7  473.48   241.7  473.53   245.7  474.65   253.6  477.03   257.6  477.73
   273.5  478.26   281.4  478.84   305.3  479.23   337.1  480.62   364.9  482.48
   376.8  484.77   386.7484.7723   404.6  486.45  416.31487.9727   416.5     488
#Mann= 7 ,-1 , 0
       0     .12       0   72.88     .07       0  169.36     .12       0
     230    .045       0   245.7     .12       0   386.7     .06       0
  416.31     .12       0
Bank Sta=230,245.7
XS Rating Curve= 0 ,0
Exp/Cntr=0.3,0.1

Type RM Length L Ch R = 1 ,10871.3 ,221.9,258,223.6
XS GIS Cut Line= 2
     2398092.114      384569.586     2398395.295      384453.356
#Sta/Elev= 30
       0     500     9.9  496.84    15.8   494.6    27.7  489.21    31.7  487.84
    39.6  484.58    43.6  482.44    51.5  479.54    55.4  478.39    59.4  477.46
    75.2  474.68    91.1  473.37  100.04473.0148   114.8   472.8   158.4  472.88
   166.3  472.47   178.2  472.35   190.1  471.88   217.8  471.58   225.7  470.11
   229.7  470.66  231.57  471.68   237.6  474.73   249.5  477.04   257.4  478.85
   265.3  480.06     293  486.49   304.9   488.3   312.8  490.22   324.7  491.99
#Mann= 5 ,-1 , 0
       0     .12       0     9.9     .08       0  100.04     .12       0
   217.8    .045       0  231.57     .12       0
Bank Sta=217.8,231.57
XS Rating Curve= 0 ,0
Exp/Cntr=0.3,0.1

Type RM Length L Ch R = 1 ,10613.3 ,149.7,141.1,124.6
XS GIS Cut Line= 2
      2398168.51      384696.933     2398438.395      384576.537
#Sta/Elev= 30
       0     498      12  493.31   20.72490.7798      24  489.64      32   485.9
    39.9  480.51    43.9  478.47    51.9  474.68    55.9  473.62    67.9  472.51
    79.9  472.19   107.8  472.63   111.8  472.17  113.74471.5783   119.4  469.95
   123.8  469.19   127.8     469   134.4  469.66   139.8  469.98   147.8   469.7
   151.8  470.05   159.7  471.63   163.7  472.01   183.7  473.41   195.7  473.79
   239.6   477.3   251.6  478.75   263.6  480.92   287.5  485.91   295.5     488
#Mann= 5 ,-1 , 0
       0     .12       0   20.72     .08       0  113.74     .12       0
   119.4    .045       0   134.4     .12       0
Bank Sta=119.4,134.4
XS Rating Curve= 0 ,0
Exp/Cntr=0.3,0.1

Type RM Length L Ch R = 1 ,10472.2 ,203,205.9,216.3
XS GIS Cut Line= 3
     2398179.894      384812.643     2398236.445      384818.071
     2398496.394      384630.637
#Sta/Elev= 30
       0  495.77    18.9  496.09    26.5  495.68    37.9   494.1    49.2  491.73
      53  490.62    56.8   489.1    72.6  480.52    76.6  478.76    84.5  473.14
    88.5  471.66    96.4   470.1   104.3  469.32  112.82 469.213     126  468.89
     141  468.64   143.8  468.61   147.8  468.81   151.8  469.81   155.7  471.31
   159.7  472.04   175.5  472.48   195.3  472.26   238.8  473.68   298.2  476.67
     310  477.86   321.9  479.61   337.7  483.27   365.4  493.01   377.3     496
#Mann= 4 ,-1 , 0
       0     .12       0  112.82     .08       0     126    .045       0
     141     .12       0
#XS Ineff= 2 , 0
          112.28  471.98
Permanent Ineff=
       F       F
Bank Sta=126,141
XS Rating Curve= 0 ,0
Exp/Cntr=0.3,0.1

Type RM Length L Ch R = 1 ,10266.3 ,295.5,330.8,365.9
XS GIS Cut Line= 3
     2398282.687      384983.109     2398339.238      384988.537
     2398638.805      384772.537
#Sta/Elev= 30
       0  478.03     3.8  477.32    11.4  475.46    18.9  473.94    22.7  473.27
    34.1   471.8    45.4  470.63    56.8     470    80.6  468.17    84.6  467.71
    88.6  466.89   95.28  465.96    96.5  465.74   100.5  465.61   116.4  465.88
   132.3   466.7   140.2  468.23   156.1  468.56     176  469.42   199.8  469.96
   247.4  471.88  272.36473.1738     307  475.26  324.93476.8234   342.7  478.72
   354.6  480.34   374.5  482.35   398.3  484.07   406.3  484.83   426.1     488
#Mann= 5 ,-1 , 0
       0     .07       0   95.28    .045       0   116.4     .06       0
  272.36     .12       0  324.93     .06       0
#XS Ineff= 2 , 0
           79.46   469.9  138.78          469.47
Permanent Ineff=
       F       F
Bank Sta=95.28,116.4
XS Rating Curve= 0 ,0
Exp/Cntr=0.3,0.1

Type RM Length L Ch R = 1 ,9935.5  ,183.4,179.2,173.9
XS GIS Cut Line= 2
     2398219.327      385024.537     2398471.778      385300.537
#Sta/Elev= 30
       0     482       4  479.85       8  478.23    25.9  474.24    47.8  470.83
    59.7  469.41    67.6  468.94    75.6  467.55    83.6  466.89   131.3  465.42
   151.2   465.5     191  464.84  202.81465.9338   206.9  465.44   214.9  463.74
   218.8  463.38   230.8   463.3   234.8   462.7   238.8  461.66   242.7  461.61
   246.7  462.58   250.7  464.11   254.7  465.09   274.6  467.87   290.5  468.51
  308.45470.2758   338.2  474.05  348.35475.9821  367.73480.5886     374     482
#Mann= 8 ,-1 , 0
       0     .12       0    25.9     .07       0  202.81     .12       0
   234.8    .045       0   246.7     .12       0  308.45     .06       0
  348.35     .12       0  367.73     .06       0
Bank Sta=234.8,246.7
XS Rating Curve= 0 ,0
Exp/Cntr=0.3,0.1

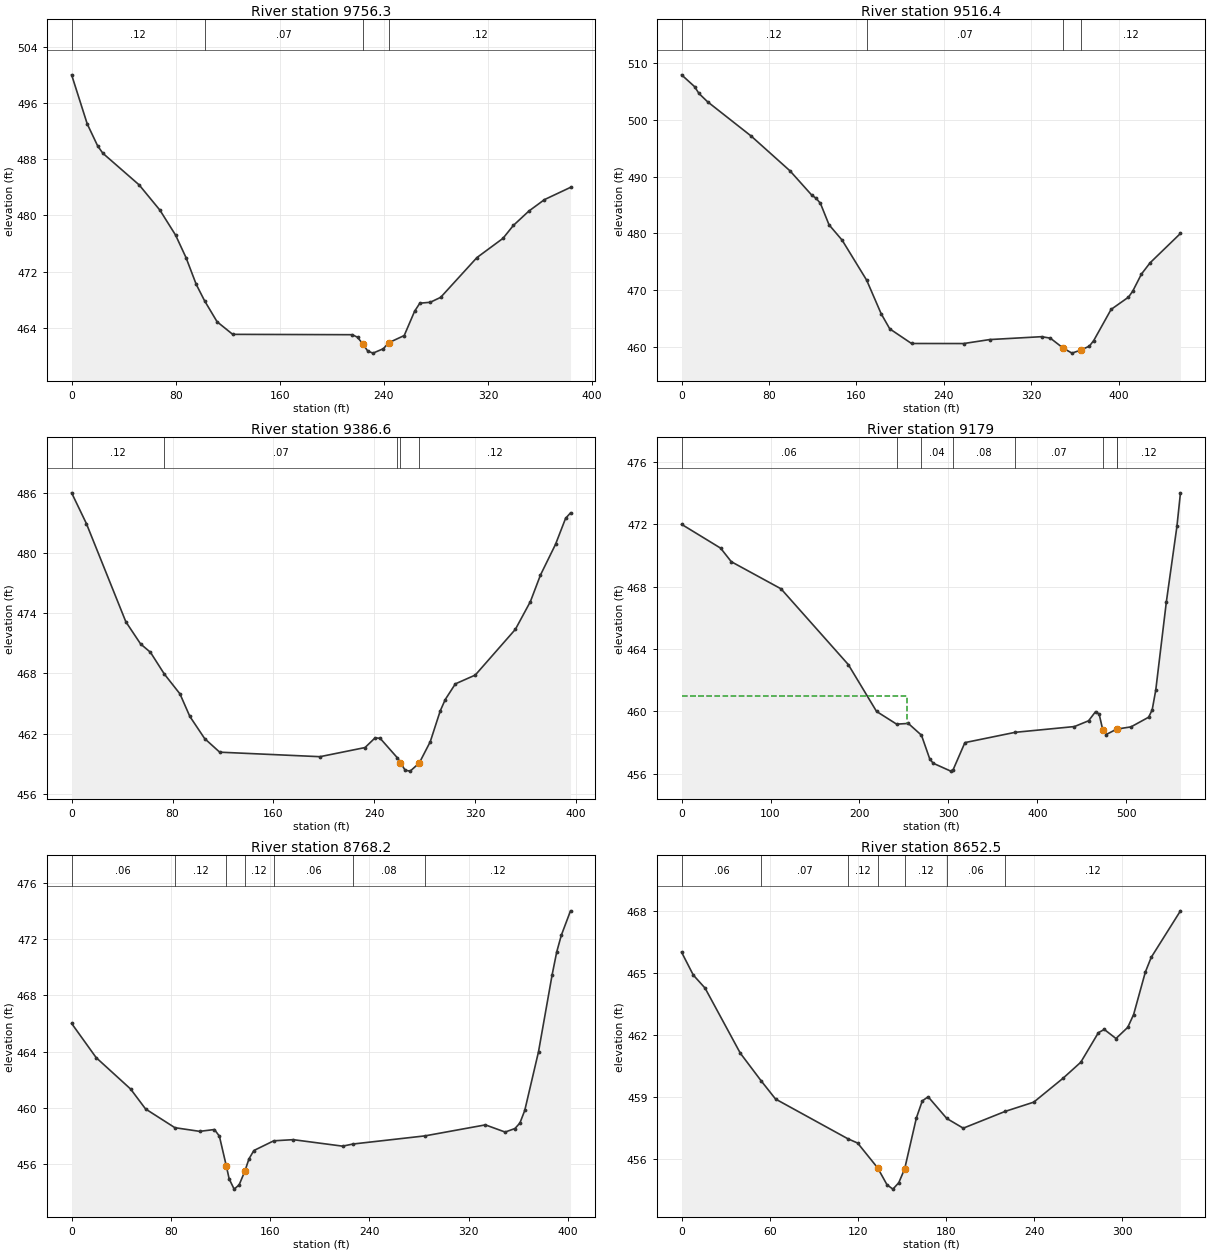
Type RM Length L Ch R = 1 ,9756.3  ,258.9,239.8,220.6
XS GIS Cut Line= 2
     2398064.598      385140.537     2398356.986      385388.537
#Sta/Elev= 30
       0     500      12  493.02      20   489.9      24  488.85    51.9  484.35
    67.9  480.75    79.9  477.21    87.9  474.02    95.8  470.19  102.19467.8709
   111.8  464.89   123.8   463.1   215.7  463.05   219.7  462.69   223.6  461.78
   227.6  460.72   231.6  460.43   239.6  461.06   243.6   461.9   255.6  462.93
   263.6  466.39   267.6  467.53   275.6  467.66   283.6  468.36   311.5  474.02
   331.5  476.75   339.5  478.59   351.4  480.63   363.4  482.26   383.4     484
#Mann= 4 ,-1 , 0
       0     .12       0  102.19     .07       0   223.6    .045       0
   243.6     .12       0
Bank Sta=223.6,243.6
XS Rating Curve= 0 ,0
Exp/Cntr=0.3,0.1

Type RM Length L Ch R = 1 ,9516.4  ,129.1,129.8,126
XS GIS Cut Line= 2
     2397901.292       385539.36     2398351.814      385464.237
#Sta/Elev= 30
       0  507.98    11.9   505.9    15.9   504.7    23.8  503.23    63.6   497.2
    99.3  491.04   119.2  486.76   123.1  486.22   127.1  485.32     135  481.53
     147  478.82  169.46 471.759   182.7  465.85   190.6  463.18   210.5   460.6
   258.2  460.59     282  461.29   329.6   461.8   337.6  461.54   349.5  459.76
   357.4   458.9   365.4  459.44   373.3  460.13   377.3  461.12   393.2  466.61
   409.1  468.77     413  469.83     421  472.85   428.9  474.83   456.7  480.01
#Mann= 4 ,-1 , 0
       0     .12       0  169.46     .07       0   349.5    .045       0
   365.4     .12       0
Bank Sta=349.5,365.4
XS Rating Curve= 0 ,0
Exp/Cntr=0.3,0.1

Type RM Length L Ch R = 1 ,9386.6  ,220.1,207.6,195.9
XS GIS Cut Line= 3
      2398026.28      385598.372     2398126.348      385615.655
     2398414.861      385559.284
#Sta/Elev= 30
       0  486.01    11.7  482.95      43  473.15    54.7  470.94    62.5  470.11
   73.43467.9527    85.9  465.96    93.7  463.72   105.5   461.5   117.4  460.15
   196.9   459.7   232.6  460.61   240.6  461.58   244.6  461.53  258.33 459.574
   260.6  459.12   264.4  458.35   268.4  458.26   275.6  459.07   284.3  461.19
   292.2  464.26   296.2   465.4   304.2  466.96     320  467.84   351.8   472.4
   363.7  475.17   371.7  477.82   383.6  480.87   391.6  483.47   395.5  484.01
#Mann= 5 ,-1 , 0
       0     .12       0   73.43     .07       0  258.33     .12       0
   260.6    .045       0   275.6     .12       0
Bank Sta=260.6,275.6
XS Rating Curve= 0 ,0
Exp/Cntr=0.3,0.1

Type RM Length L Ch R = 1 ,9179    ,406.8,410.9,413.5
XS GIS Cut Line= 3
     2397884.114       385993.19     2398029.335      385949.402
     2398365.023      385715.628
#Sta/Elev= 30
       0     472    43.9  470.47    55.9   469.6   111.8  467.86   187.4     463
   219.2  459.99  241.74459.1752   254.9  459.22  269.68458.4636   278.8  456.97
   282.7  456.67   302.6  456.16  305.23456.2455   318.5  457.99  375.02458.6507
   441.6  459.02   457.5  459.39   465.4  459.98   469.4  459.82   473.4  458.82
   477.3  458.51   489.3  458.86  489.52458.8606   505.2     459     525  459.62
     529  460.09     533  461.35   544.9  467.01   556.8  471.86   560.8  474.02
#Mann= 8 ,-1 , 0
       0     .06       0  241.74     .12       0  269.68     .04       0
  305.23     .08       0  375.02     .07       0   473.4    .045       0
   489.3     .07       0  489.52     .12       0
#XS Ineff= 2 , 0
          253.87  461.01
Permanent Ineff=
       F       F
Bank Sta=473.4,489.3
XS Rating Curve= 0 ,0
Exp/Cntr=0.3,0.1

Type RM Length L Ch R = 1 ,8768.2  ,112.9,115.7,118.6
XS GIS Cut Line= 3
     2398115.452      386084.537     2398433.284      385904.585
     2398469.006      385895.645
#Sta/Elev= 30
       0     466    19.8  463.57    47.6  461.34    59.6  459.93   83.24   458.6
   103.2  458.34   115.1  458.47   119.1     458   124.7  455.88     127  454.96
     131  454.24     135  454.54   139.7  455.53   142.9  456.38   146.9  456.98
  162.93457.6697   178.6  457.75   218.4  457.29  226.78457.4412  284.86458.0197
   333.5   458.8   349.4  458.29   357.3  458.54   361.3  458.93   365.2  459.82
   376.3  463.99   387.3  469.46     391  471.08   394.7  472.26   402.1  473.99
#Mann= 7 ,-1 , 0
       0     .06       0   83.24     .12       0   124.7    .045       0
   139.7     .12       0  162.93     .06       0  226.78     .08       0
  284.86     .12       0
Bank Sta=124.7,139.7
XS Rating Curve= 0 ,0
Exp/Cntr=0.3,0.1

Type RM Length L Ch R = 1 ,8652.5  ,166.3,166.6,166.6
XS GIS Cut Line= 2
     2398180.626      386164.025     2398488.114      386019.562
#Sta/Elev= 30
       0     466       8  464.89      16  464.26      40  461.11   54.32459.7596
      64  458.89  113.28456.9659   119.9  456.76   133.5  455.56   139.9  454.74
   143.9  454.53   147.9  454.84   151.9  455.51   159.9  457.98   163.9   458.8
   167.9     459   180.6457.9492   191.8  457.48  220.39458.2933   239.8  458.74
   259.8   459.9   271.8  460.67   283.8   462.1   287.8  462.26   295.8  461.82
   303.8  462.36   307.8  462.98   315.8  465.04   319.8  465.75   339.7     468
#Mann= 7 ,-1 , 0
       0     .06       0   54.32     .07       0  113.28     .12       0
   133.5    .045       0   151.9     .12       0   180.6     .06       0
  220.39     .12       0
Bank Sta=133.5,151.9
XS Rating Curve= 0 ,0
Exp/Cntr=0.3,0.1