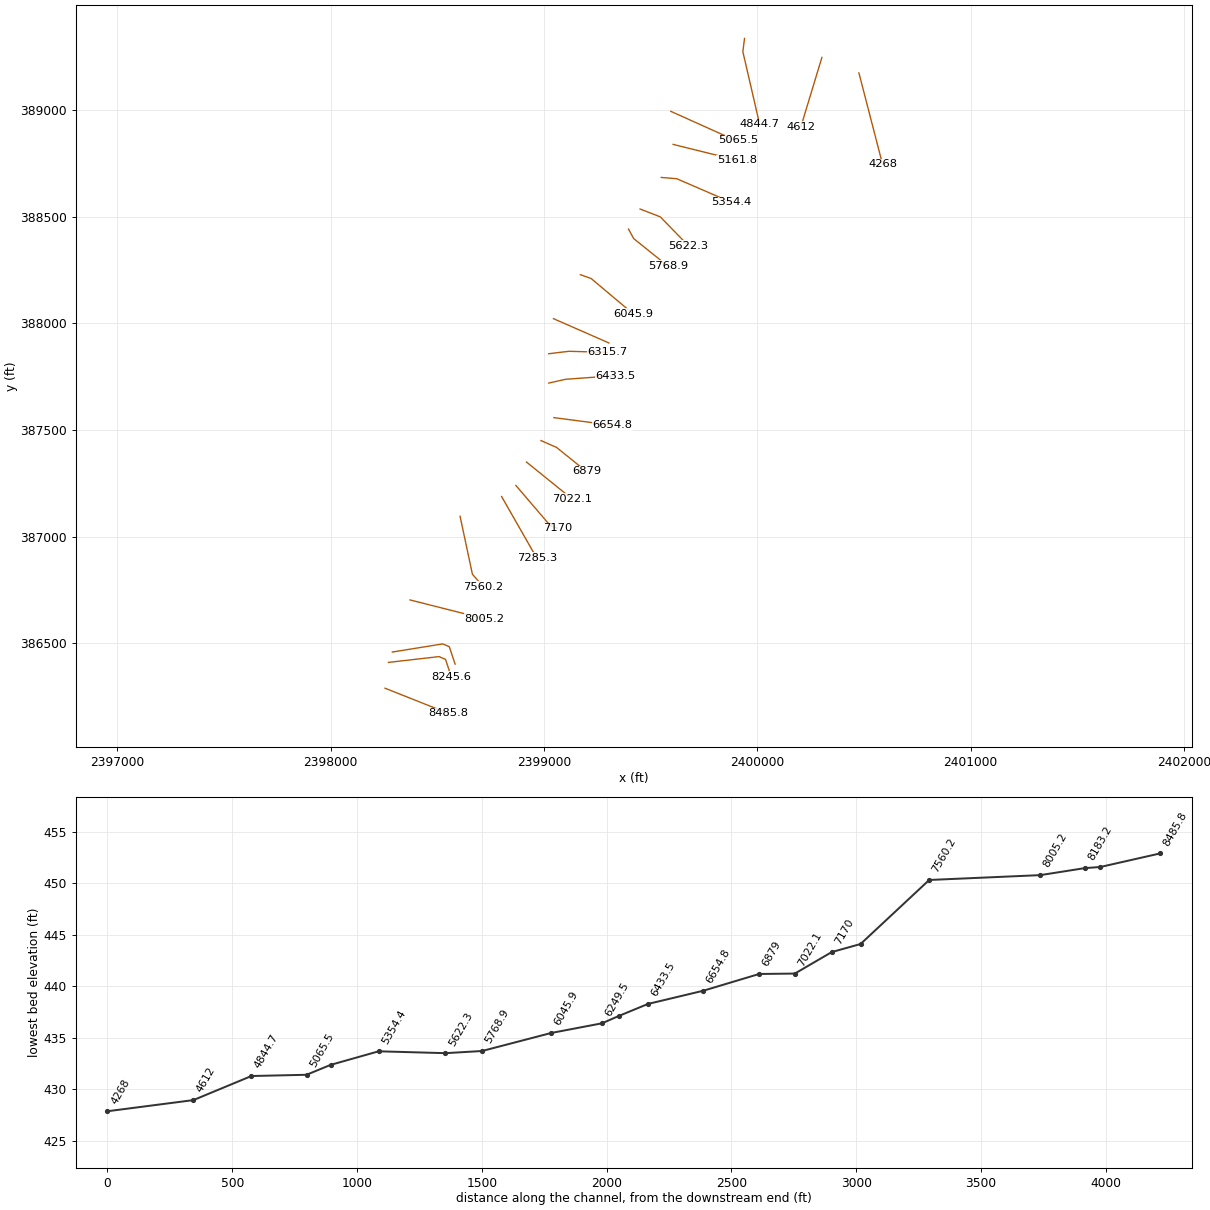
HEC-RAS study TULLISBRRN.prj: TULLISBRRN

--- TULLISBRRN.g01 (geometry) --- (continued)

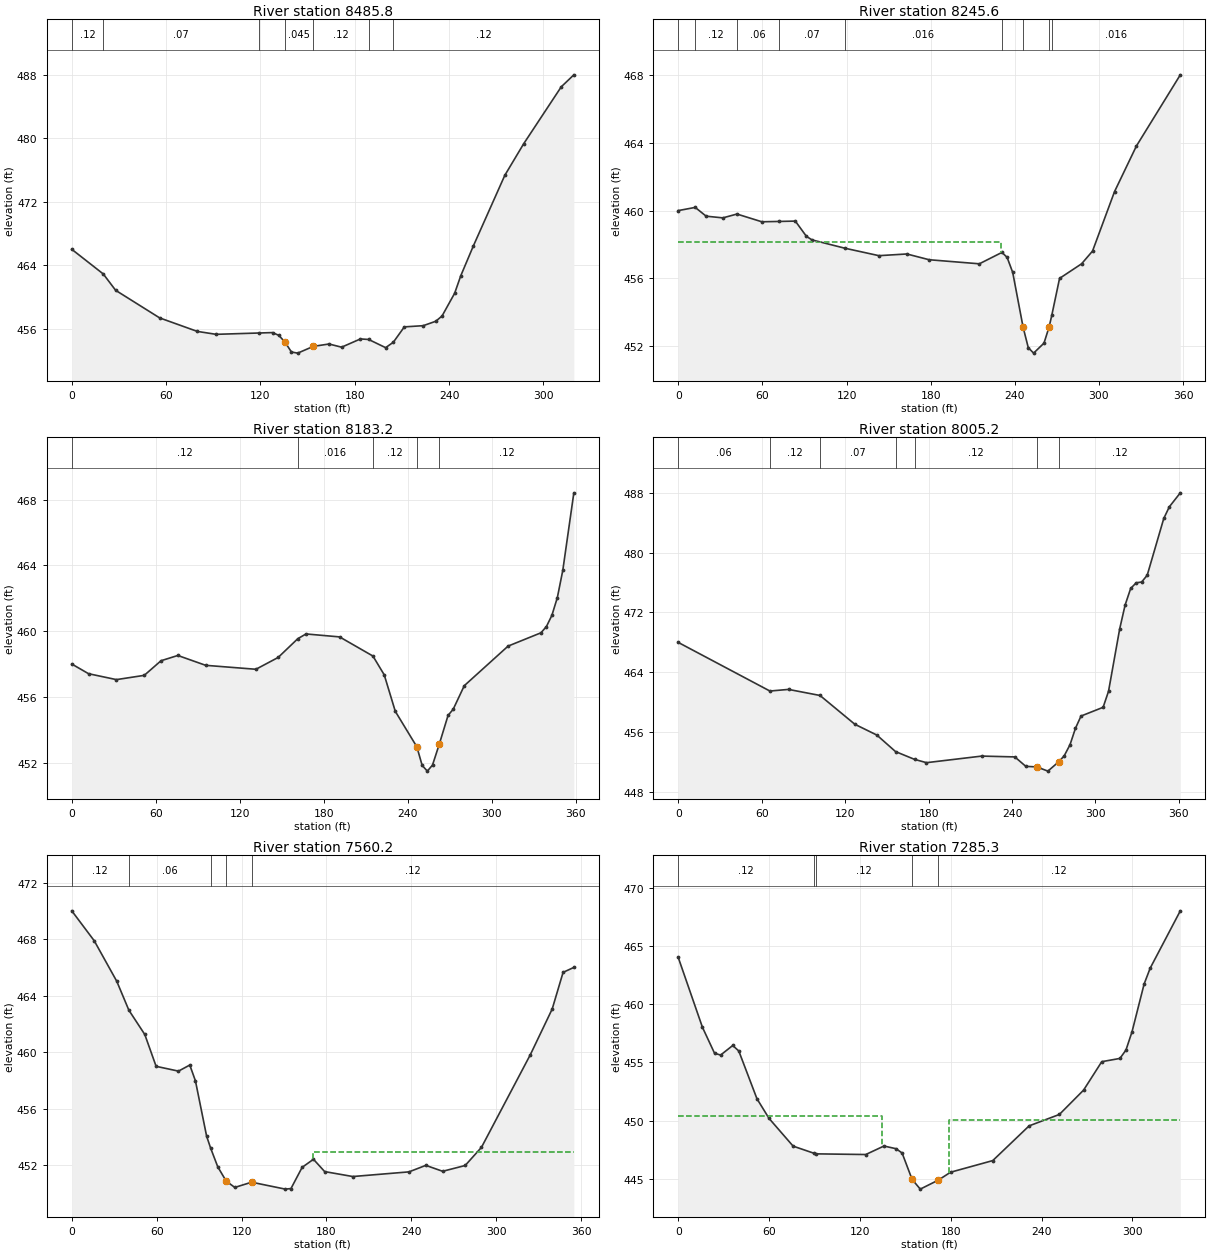
Type RM Length L Ch R = 1 ,8485.8  ,235.4,240.2,237.1
XS GIS Cut Line= 2
     2398254.814      386289.837     2398551.559      386171.982
#Sta/Elev= 30
       0     466   20.04462.8898    27.9  460.83    55.9  457.35    79.8  455.65
    91.8  455.28  118.76455.4459   127.7   455.5   131.7  455.15   135.7  454.27
   139.7  453.05   143.7  452.91   153.6  453.76   163.6  454.06   171.6  453.66
   183.6   454.7  188.83454.6308   199.6   453.6   204.5454.2815   211.5  456.22
   223.5  456.37   231.5  456.93   235.5   457.6   243.5  460.46   247.4  462.67
   255.4  466.43   275.4  475.33   287.4  479.31   311.3  486.49   319.3     488
#Mann= 7 ,-1 , 0
       0     .12       0   20.04     .07       0  118.76     .12       0
   135.7    .045       0   153.6     .12       0  188.83     .06       0
   204.5     .12       0
Bank Sta=135.7,153.6
XS Rating Curve= 0 ,0
Exp/Cntr=0.3,0.1

Type RM Length L Ch R = 1 ,8245.6  ,62,62.4,59.8
XS GIS Cut Line= 4
     2398270.554      386410.977     2398507.512      386438.099
     2398538.219      386424.919     2398565.435      386343.217
#Sta/Elev= 30
       0     460   12.11460.1879    19.9  459.67    31.8  459.57   41.88 459.796
    59.6  459.34   71.65459.3592    83.5  459.38    91.4  458.48    95.4  458.27
  118.81  457.78   143.1  457.34     163  457.44   178.9   457.1   214.7  456.86
  230.82457.5325   234.5  457.24   238.5  456.35   245.9  453.12   249.6  451.91
   253.4  451.59   260.8  452.18   264.5  453.15  266.38453.8309   271.9     456
   287.6  456.86   295.4  457.61   311.1  461.12   326.7  463.81     358  468.01
#Mann= 9 ,-1 , 0
       0     .06       0   12.11     .12       0   41.88     .06       0
   71.65     .07       0  118.81    .016       0  230.82     .12       0
   245.9    .045       0   264.5     .12       0  266.38    .016       0
#XS Ineff= 2 , 0
          230.19  458.17
Permanent Ineff=
       F       F
Bank Sta=245.9,264.5
XS Rating Curve= 0 ,0
Exp/Cntr=0.3,0.1

Type RM Length L Ch R = 1 ,8183.2  ,180.6,178,186.1
XS GIS Cut Line= 4
     2398288.982      386459.669     2398525.154      386497.717
     2398555.861      386484.537     2398583.077      386402.835
#Sta/Elev= 30
       0     458      12  457.41    31.9  457.05    51.8  457.31    63.8   458.2
    75.8  458.52    95.7  457.92   131.6  457.68   147.5   458.4  161.52 459.541
   167.4  459.83   191.4  459.65  215.22458.4846   223.3  457.34   231.2  455.12
   246.6  452.96   250.4  451.83   254.1  451.48   257.8  451.85   262.6  453.11
   268.9  454.87   272.6  455.25   280.5  456.68   311.8  459.09   335.3   459.9
   339.2  460.28   343.1  460.96     347  462.04   350.9   463.7   358.8  468.42
#Mann= 5 ,-1 , 0
       0     .12       0  161.52    .016       0  215.22     .12       0
   246.6    .045       0   262.6     .12       0
Bank Sta=246.6,262.6
XS Rating Curve= 0 ,0
Exp/Cntr=0.3,0.1

Type RM Length L Ch R = 1 ,8005.2  ,470.3,445,420
XS GIS Cut Line= 2
     2398371.504      386703.927     2398721.442       386615.21
#Sta/Elev= 30
       0     468   65.91461.5031    79.3  461.72  101.95  460.91     127  457.06
   142.8  455.62  156.23453.4129   169.9452.3712   178.5  451.93   218.2  452.81
     242   452.7   249.9  451.44   257.9  451.36   265.8   450.8   273.7  452.07
   277.5  452.84   281.7  454.33   285.6  456.52   289.6  458.16   305.5  459.33
   309.4  461.48   317.4   469.8   321.3  472.99   325.3  475.21   329.3  475.97
   333.2  476.07   337.2  476.98   349.1  484.56   353.1  486.12     361  487.99
#Mann= 7 ,-1 , 0
       0     .06       0   65.91     .12       0  101.95     .07       0
  156.23     .06       0   169.9     .12       0   257.9    .045       0
   273.7     .12       0
Bank Sta=257.9,273.7
XS Rating Curve= 0 ,0
Exp/Cntr=0.3,0.1

Type RM Length L Ch R = 1 ,7560.2  ,267.6,275,281.6
XS GIS Cut Line= 3
     2398606.221      387096.332     2398664.188      386824.463
     2398714.389      386766.262
#Sta/Elev= 30
       0     470    15.9  467.88    31.8  465.02   40.34462.9784    51.6  461.26
    59.6  459.01    75.4  458.67    83.4   459.1    87.4  457.98    95.3  454.07
   98.13453.2281   103.2   451.9  109.11   450.9   115.2  450.45   127.1  450.82
   150.9  450.33   154.9  450.37   162.8  451.87   170.8  452.44   178.7  451.57
   198.6  451.22   238.3  451.55   250.2  452.01   262.1  451.59     278     452
   289.5  453.28   324.1  459.84   339.5  463.06   347.2  465.65   354.8     466
#Mann= 5 ,-1 , 0
       0     .12       0   40.34     .06       0   98.13     .12       0
  109.11    .045       0   127.1     .12       0
#XS Ineff= 2 , 0
                          170.72          452.92
Permanent Ineff=
       F       F
Bank Sta=109.11,127.1
XS Rating Curve= 0 ,0
Exp/Cntr=0.3,0.1

Type RM Length L Ch R = 1 ,7285.3  ,110.6,115.3,119.8
XS GIS Cut Line= 2
     2398801.031      387188.537     2398965.673      386900.537
#Sta/Elev= 30
       0     464      16     458      24  455.77      28  455.62      36  456.44
      40  455.97      52  451.87      60  450.18    75.9   447.8   89.84447.1821
    91.1 447.138   123.9  447.08   135.9  447.81   143.9  447.58   147.9  447.21
  154.48  444.95   159.9  444.11   171.9  444.89   179.9  445.56   207.8  446.56
   231.8  449.54   251.8  450.52   267.8  452.61   279.8  455.05   291.8  455.33
   295.8  456.05   299.8  457.62   307.8  461.72   311.8  463.08   331.7     468
#Mann= 5 ,-1 , 0
       0     .12       0   89.84     .06       0    91.1     .12       0
  154.48    .045       0   171.9     .12       0
#XS Ineff= 2 , 0
          134.74  450.35  178.79          450.03
Permanent Ineff=
       F       F
Bank Sta=154.48,171.9
XS Rating Curve= 0 ,0
Exp/Cntr=0.3,0.1

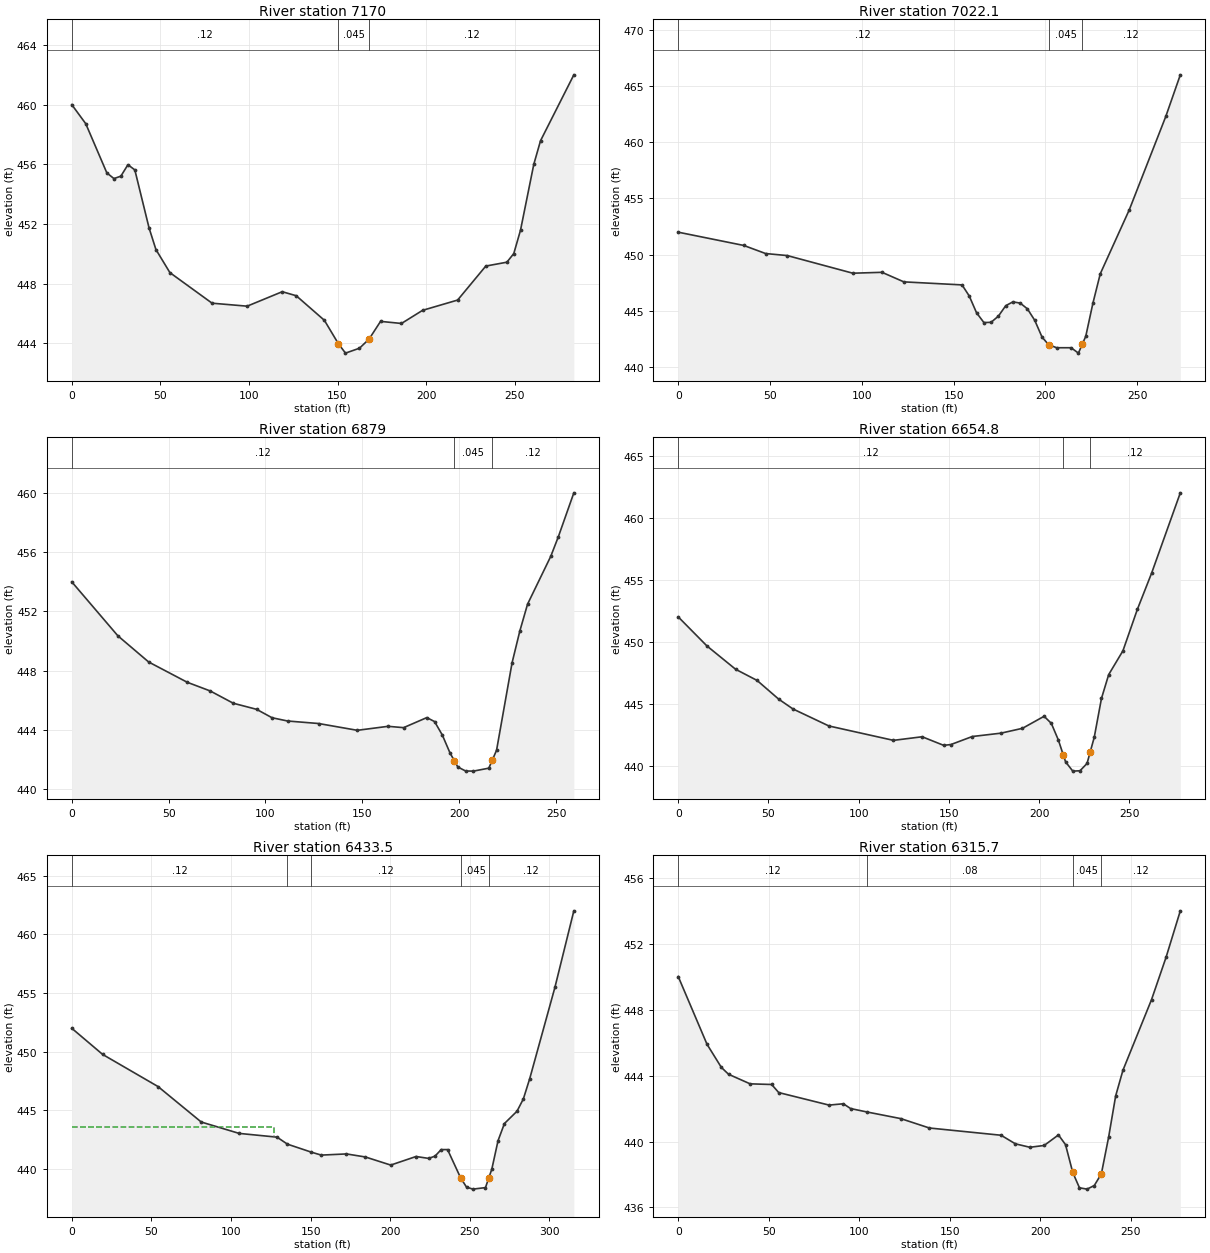
Type RM Length L Ch R = 1 ,7170    ,143.7,148,152.3
XS GIS Cut Line= 3
     2398868.114      387240.338     2399030.373      387050.795
     2399062.697      387040.537
#Sta/Elev= 30
       0     460     7.9  458.72    19.8  455.42    23.8  455.04    27.7   455.2
    31.7  455.97    35.6  455.62    43.6  451.74    47.5  450.28    55.4  448.73
    79.2  446.68      99  446.48   118.8  447.45   126.7  447.18   142.6  445.53
   150.5  443.96   154.5  443.33   162.4  443.66   167.8  444.27   174.3  445.46
   186.1  445.32     198   446.2   217.8  446.89   233.7  449.17   245.6  449.43
   249.5  450.01   253.3  451.58   260.8     456   264.6  457.58   283.4     462
#Mann= 3 ,-1 , 0
       0     .12       0   150.5    .045       0   167.8     .12       0
Bank Sta=150.5,167.8
XS Rating Curve= 0 ,0
Exp/Cntr=0.3,0.1

Type RM Length L Ch R = 1 ,7022.1  ,143.2,143.1,142.9
XS GIS Cut Line= 2
     2398917.793      387350.216     2399130.426      387178.225
#Sta/Elev= 30
       0     452    35.7  450.82    47.6   450.1    59.4  449.92    95.1  448.35
     111  448.43   122.9  447.58   154.6  447.31   158.5  446.33   162.5  444.83
   166.5  443.96   170.4  443.98   174.4  444.53   178.4  445.46   182.3   445.8
   186.3  445.69   190.2  445.18   194.2  444.16   198.2  442.66   201.7     442
   206.1  441.72     214  441.72     218  441.24  220.15  442.05     222  442.74
   225.9  445.69   229.9   448.3   245.7  453.99   265.6   462.3   273.5     466
#Mann= 3 ,-1 , 0
       0     .12       0   201.7    .045       0  220.15     .12       0
Bank Sta=201.7,220.15
XS Rating Curve= 0 ,0
Exp/Cntr=0.3,0.1

Type RM Length L Ch R = 1 ,6879    ,211.8,224.2,236.6
XS GIS Cut Line= 3
     2398985.812      387450.839     2399058.557       387418.98
     2399198.549      387306.102
#Sta/Elev= 30
       0     454    23.8  450.35    39.7  448.58    59.6  447.21    71.5  446.62
    83.4  445.79    95.4  445.38   103.4  444.81   111.4  444.59   127.4  444.42
   147.4  443.96   163.3  444.23   171.3  444.14   183.3  444.82   187.3  444.55
   191.3  443.64   195.3  442.42  197.48  441.91   199.3  441.48   203.3  441.21
   207.3   441.2   215.3   441.4  217.05  441.93   219.3  442.61   227.3  448.52
   231.3  450.67   235.3  452.49   247.3  455.73   251.2  457.05   259.2  460.02
#Mann= 3 ,-1 , 0
       0     .12       0  197.48    .045       0  217.05     .12       0
Bank Sta=197.48,217.05
XS Rating Curve= 0 ,0
Exp/Cntr=0.3,0.1

Type RM Length L Ch R = 1 ,6654.8  ,216.7,221.3,225.8
XS GIS Cut Line= 2
     2399046.101      387558.551     2399322.079      387522.502
#Sta/Elev= 30
       0     452    15.9  449.66    31.8  447.78    43.7  446.88    55.7  445.37
    63.6  444.58    83.5  443.21   119.3  442.05   135.2  442.34   147.1  441.65
   151.1  441.71     163  442.36   178.9  442.63   190.8  443.02   202.8  443.99
   206.8  443.42   210.7  442.08   213.4  440.89   214.7  440.32   218.7  439.57
   222.7   439.6   226.6  440.19   228.4  441.14   230.6   442.3   234.6  445.43
   238.6  447.35   246.5  449.27   254.5  452.61   262.4  455.53   278.3     462
#Mann= 3 ,-1 , 0
       0     .12       0   213.4    .045       0   228.4     .12       0
Bank Sta=213.4,228.4
XS Rating Curve= 0 ,0
Exp/Cntr=0.3,0.1

Type RM Length L Ch R = 1 ,6433.5  ,120.2,117.9,115.7
XS GIS Cut Line= 3
     2399022.039      387720.537     2399101.371      387738.311
     2399334.785      387755.208
#Sta/Elev= 30
       0     452    19.4  449.77    54.2  447.03    81.3  444.01   105.1  443.04
   128.9  442.72  135.46442.1218  150.41 441.443   156.7  441.19   172.5  441.29
   184.4  441.03   200.3  440.34   216.2  441.07   224.1  440.91   228.1   441.1
     232  441.66     236  441.66   244.2  439.25   247.9  438.46   251.9  438.29
   259.8  438.42  261.83  439.22   263.8     440   267.7  442.42   271.7  443.88
   279.6  444.93   283.6  445.98   287.6  447.71   303.4  455.48   315.3  462.01
#Mann= 5 ,-1 , 0
       0     .12       0  135.46     .08       0  150.41     .12       0
   244.2    .045       0  261.83     .12       0
#XS Ineff= 2 , 0
          127.14  443.56
Permanent Ineff=
       F       F
Bank Sta=244.2,261.83
XS Rating Curve= 0 ,0
Exp/Cntr=0.3,0.1

Type RM Length L Ch R = 1 ,6315.7  ,75,66.2,57.2
XS GIS Cut Line= 3
     2399021.601      387858.024     2399116.114      387869.475
     2399298.106      387864.537
#Sta/Elev= 30
       0  450.01    15.9   445.9    23.8   444.5    27.8  444.08    39.7   443.5
    51.6  443.46    55.5  442.97    83.3  442.21    91.2  442.29    95.2     442
  104.12441.7949   122.9  441.39   138.7  440.82   178.3  440.38   186.2  439.86
   194.2  439.65   202.1  439.76     210   440.4   213.9  439.81   217.9  438.12
   221.6  437.19   225.8  437.11   229.8  437.33   233.7  438.04   237.7  440.26
   241.6  442.77   245.6  444.32   261.4  448.61   269.4  451.17   277.3     454
#Mann= 4 ,-1 , 0
       0     .12       0  104.12     .08       0   217.9    .045       0
   233.7     .12       0
Bank Sta=217.9,233.7
XS Rating Curve= 0 ,0
Exp/Cntr=0.3,0.1

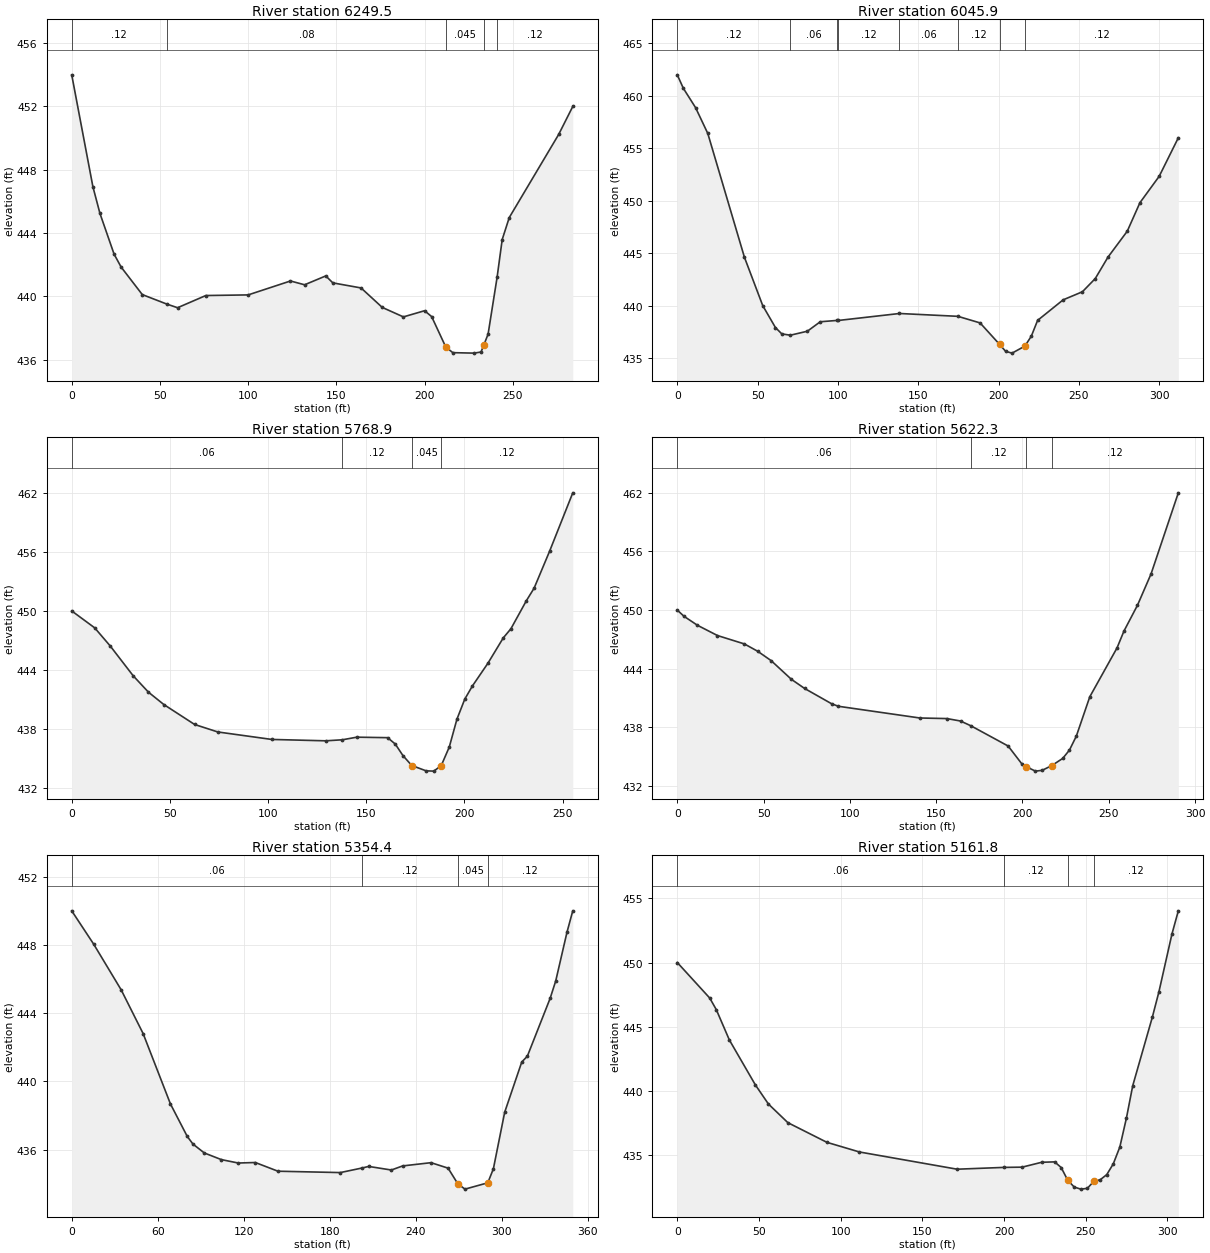
Type RM Length L Ch R = 1 ,6249.5  ,210,203.6,197.3
XS GIS Cut Line= 2
     2399044.114      388022.575     2399304.192      387908.537
#Sta/Elev= 30
       0     454      12  446.93      16  445.24      24  442.67      28  441.85
      40  440.11   53.96439.5077      60  439.28      76  440.05     100  440.09
     124  440.97     132  440.73     144  441.29     148  440.85     164  440.53
     176   439.3     188   438.7     200  439.09     204  438.72     212   436.8
     216  436.44     228  436.41     232  436.48  233.57  436.92     236  437.61
   241.1441.1975     244  443.59     248  444.98     276  450.23     284     452
#Mann= 5 ,-1 , 0
       0     .12       0   53.96     .08       0     212    .045       0
  233.57     .08       0   241.1     .12       0
Bank Sta=212,233.57
XS Rating Curve= 0 ,0
Exp/Cntr=0.3,0.1

Type RM Length L Ch R = 1 ,6045.9  ,276.2,276.9,277.5
XS GIS Cut Line= 3
     2399170.331      388228.537     2399220.508      388210.984
     2399418.613      388044.537
#Sta/Elev= 30
       0     462     3.8  460.71    11.4  458.87      19  456.41    41.8  444.61
    53.2     440    61.1  437.91    65.1   437.3   70.44437.1801      81  437.56
      89  438.46   99.68438.5894  100.31438.5845  138.33439.2478  174.67438.9786
   188.5  438.35   200.6  436.31   204.4  435.64   208.4  435.47   216.4  436.14
   220.4  437.09   224.3  438.59   240.2  440.55   252.2  441.32   260.2  442.58
   268.1  444.62   280.1  447.09     288  449.81     300  452.33   311.9     456
#Mann= 8 ,-1 , 0
       0     .12       0   70.44     .06       0   99.68     .08       0
  100.31     .12       0  138.33     .06       0  174.67     .12       0
   200.6    .045       0   216.4     .12       0
Bank Sta=200.6,216.4
XS Rating Curve= 0 ,0
Exp/Cntr=0.3,0.1

Type RM Length L Ch R = 1 ,5768.9  ,149.6,146.6,144.1
XS GIS Cut Line= 3
     2399396.114       388442.45     2399420.325      388397.728
     2399579.754      388269.957
#Sta/Elev= 30
       0     450    11.7  448.28    19.6  446.44    31.3  443.41    39.1  441.74
    46.9  440.49    62.6  438.46    74.4   437.7   101.9  436.94   129.4   436.8
  137.85436.9054   145.2  437.17   160.9  437.12   164.8  436.47   168.7   435.3
   173.2  434.29   180.5  433.75   184.4  433.72   188.2  434.28   192.3  436.17
   196.2     439   200.2  441.04   204.1  442.38     212  444.69   219.8  447.26
   223.7  448.19   231.6  451.05   235.5  452.31   243.4  456.07   255.2     462
#Mann= 4 ,-1 , 0
       0     .06       0  137.85     .12       0   173.2    .045       0
   188.2     .12       0
Bank Sta=173.2,188.2
XS Rating Curve= 0 ,0
Exp/Cntr=0.3,0.1

Type RM Length L Ch R = 1 ,5622.3  ,257.3,267.9,276.9
XS GIS Cut Line= 3
     2399450.378      388536.537     2399544.605      388500.046
     2399676.722      388364.537
#Sta/Elev= 30
       0     450     3.9  449.36    11.7  448.44    23.3  447.39    38.9  446.53
    46.6  445.78    54.4  444.82    66.1  442.91    73.8  441.97    89.4  440.41
    93.3  440.15   140.5  438.95   156.2  438.89   164.1  438.64  170.17438.1461
   191.7  436.08   199.6  434.26     202  433.98   207.5  433.51   211.4  433.59
     217  434.08   223.3  434.81   227.2  435.66   231.2  437.09     239  441.12
   254.8  446.13   258.8  447.85   266.6  450.48   274.5   453.7   290.3     462
#Mann= 4 ,-1 , 0
       0     .06       0  170.17     .12       0     202    .045       0
     217     .12       0
Bank Sta=202,217
XS Rating Curve= 0 ,0
Exp/Cntr=0.3,0.1

Type RM Length L Ch R = 1 ,5354.4  ,189.8,192.6,196.2
XS GIS Cut Line= 3
     2399549.677      388684.537     2399622.174      388678.597
     2399876.255      388568.678
#Sta/Elev= 30
       0     450    15.3  448.05    34.5  445.37    49.8  442.81    68.9  438.68
    80.6  436.78    84.6  436.33    92.5  435.81   104.4  435.42   116.2  435.22
   128.1  435.25   143.9  434.74   187.4  434.66  202.85434.9328   207.2  435.02
     223  434.81   230.9  435.05   250.7  435.24   262.6  434.92   269.4     434
   274.4  433.69   290.3  434.06   294.2  434.88   302.1   438.2     314  441.14
   317.9  441.48   333.8  444.87   337.7  445.89   345.6  448.76   349.6     450
#Mann= 4 ,-1 , 0
       0     .06       0  202.85     .12       0   269.4    .045       0
   290.3     .12       0
Bank Sta=269.4,290.3
XS Rating Curve= 0 ,0
Exp/Cntr=0.3,0.1

Type RM Length L Ch R = 1 ,5161.8  ,100.5,96.3,92
XS GIS Cut Line= 2
     2399605.233      388839.466      2399902.96      388765.691
#Sta/Elev= 30
       0     450    19.9  447.23    23.9  446.33    31.9  443.97    47.8  440.48
    55.8  438.99    67.7  437.54    91.6  436.01   111.5  435.26   171.3  433.92
  199.94  434.06   211.1  434.08   223.1  434.46     231  434.49     235  434.05
     239  433.06     243  432.53     247  432.37     251  432.43     255  432.98
   258.9   433.1   262.9   433.5   266.9  434.34   270.9  435.65   274.9  437.88
   278.8  440.42   290.8  445.75   294.8  447.71   302.8  452.22   306.7  454.02
#Mann= 4 ,-1 , 0
       0     .06       0  199.94     .12       0     239    .045       0
     255     .12       0
Bank Sta=239,255
XS Rating Curve= 0 ,0
Exp/Cntr=0.3,0.1

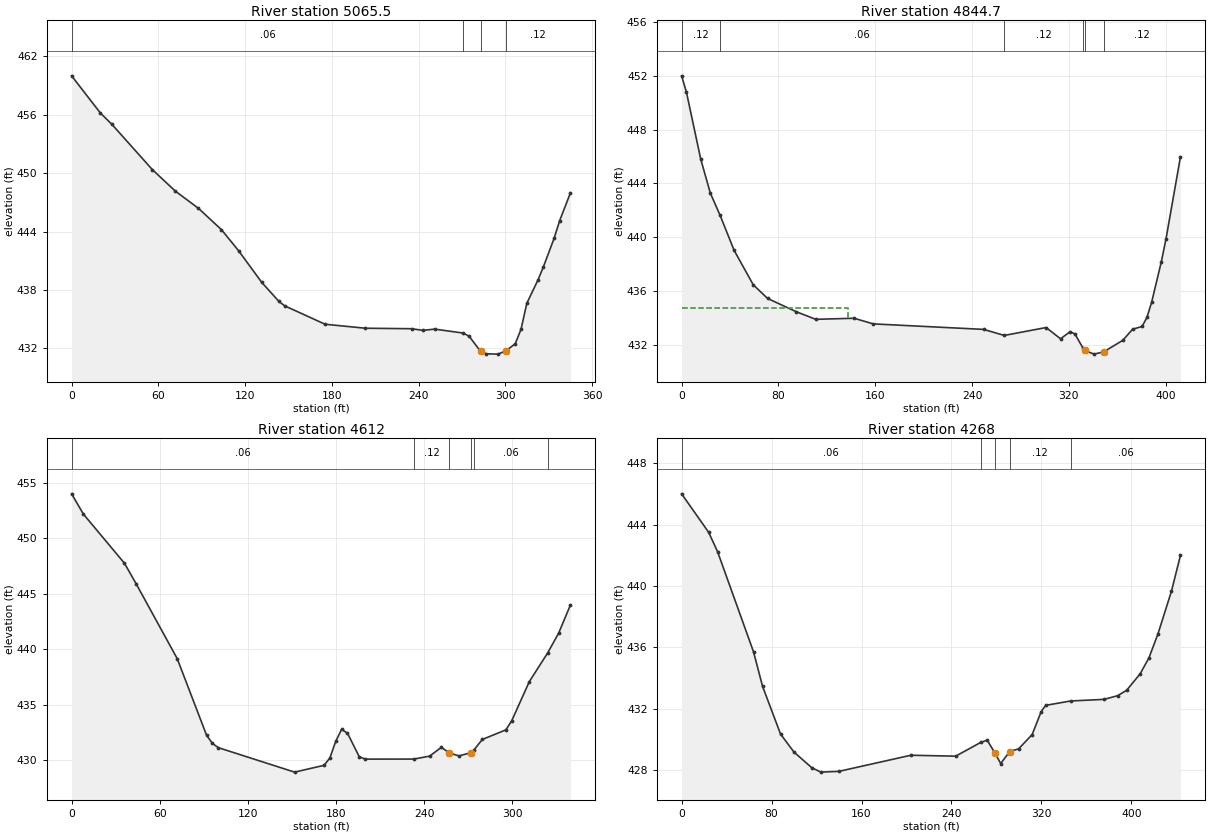
Type RM Length L Ch R = 1 ,5065.5  ,243.5,220.8,196.4
XS GIS Cut Line= 3
     2399594.184      388994.606     2399884.873      388863.778
     2399910.449      388858.202
#Sta/Elev= 30
       0     460    19.9  456.18    27.9  455.01    55.8  450.37    71.7  448.16
    87.7  446.39   103.6   444.2   115.6  442.01   131.5  438.78   143.4  436.82
   147.4  436.37   175.3  434.48   203.2  434.07   235.1  434.02   243.1  433.85
     251  433.98  270.76433.5772   274.9  433.25   282.9  431.68   286.9  431.44
   294.9  431.41   300.3  431.74   306.8  432.48   310.8  433.96   314.8  436.63
   322.5  439.02   326.2  440.35   333.7  443.31   337.5  445.11     345  447.99
#Mann= 4 ,-1 , 0
       0     .06       0  270.76     .12       0   282.9    .045       0
   300.3     .12       0
Bank Sta=282.9,300.3
XS Rating Curve= 0 ,0
Exp/Cntr=0.3,0.1

Type RM Length L Ch R = 1 ,4844.7  ,244.4,232.7,220.9
XS GIS Cut Line= 3
     2399939.923      389336.728     2399932.114       389274.01
     2400010.713      388933.939
#Sta/Elev= 30
       0     452       4  450.78    15.8   445.8    23.7  443.28   31.84441.6102
    43.4  439.01    59.2  436.45    71.1  435.43    94.9  434.44   110.8  433.88
   142.5  433.96   158.4  433.54   249.6  433.13  266.62432.6814   301.2  433.27
   313.1  432.43     321  432.96     325  432.79  331.69431.7313   332.9  431.57
   340.8  431.29   348.8  431.46   364.6  432.32   372.6  433.14   380.5  433.35
   384.5  434.02   388.4  435.16   396.4  438.17   400.3  439.89   412.2  445.98
#Mann= 6 ,-1 , 0
       0     .12       0   31.84     .06       0  266.62     .12       0
  331.69     .06       0   332.9    .045       0   348.8     .12       0
#XS Ineff= 2 , 0
          137.25  434.69
Permanent Ineff=
       F       F
Bank Sta=332.9,348.8
XS Rating Curve= 0 ,0
Exp/Cntr=0.3,0.1

Type RM Length L Ch R = 1 ,4612    ,329.4,343.9,358.1
XS GIS Cut Line= 2
     2400302.686      389247.108     2400204.114      388922.152
#Sta/Elev= 30
       0  453.99       8  452.17      36  447.74      44  445.88    71.9  439.16
    91.9  432.26    95.9  431.53    99.9  431.15   151.8  428.95   171.8  429.56
   175.8  430.22   179.8  431.72   183.8   432.8   187.8  432.45   195.8  430.34
   199.8  430.12  232.95 430.125   243.7  430.39   251.7  431.18   257.2  430.67
   263.7  430.41   272.2  430.71  273.76430.9284   279.6  431.89   295.6  432.75
   299.6  433.57   311.6   437.1  324.02439.6619   331.6  441.47   339.6     444
#Mann= 6 ,-1 , 0
       0     .06       0  232.95     .12       0   257.2    .045       0
   272.2     .12       0  273.76     .06       0  324.02     .12       0
Bank Sta=257.2,272.2
XS Rating Curve= 0 ,0
Exp/Cntr=0.3,0.1

Type RM Length L Ch R = 1 ,4268    ,375.4,393,409.9
XS GIS Cut Line= 2
     2400476.114      389174.865     2400587.345      388745.306
#Sta/Elev= 30
       0     446      24   443.5      32  442.23      64   435.7      72  433.46
      88  430.35    99.9  429.18   115.9  428.15   123.9  427.87   139.9  427.92
   203.9  428.97   243.8  428.91  266.09429.8089   271.8  429.95  278.55  429.13
   283.8  428.43   291.8  429.21   299.8  429.39   311.8  430.32   319.8  431.81
   323.8  432.22  345.97432.5046   375.8  432.61   387.8  432.85   395.8   433.2
   407.8  434.27   415.7  435.32   423.7  436.88   435.7  439.66   443.7     442
#Mann= 5 ,-1 , 0
       0     .06       0  266.09     .12       0  278.55    .045       0
   291.8     .12       0  345.97     .06       0
Bank Sta=278.55,291.8
XS Rating Curve= 0 ,0
Exp/Cntr=0.3,0.1