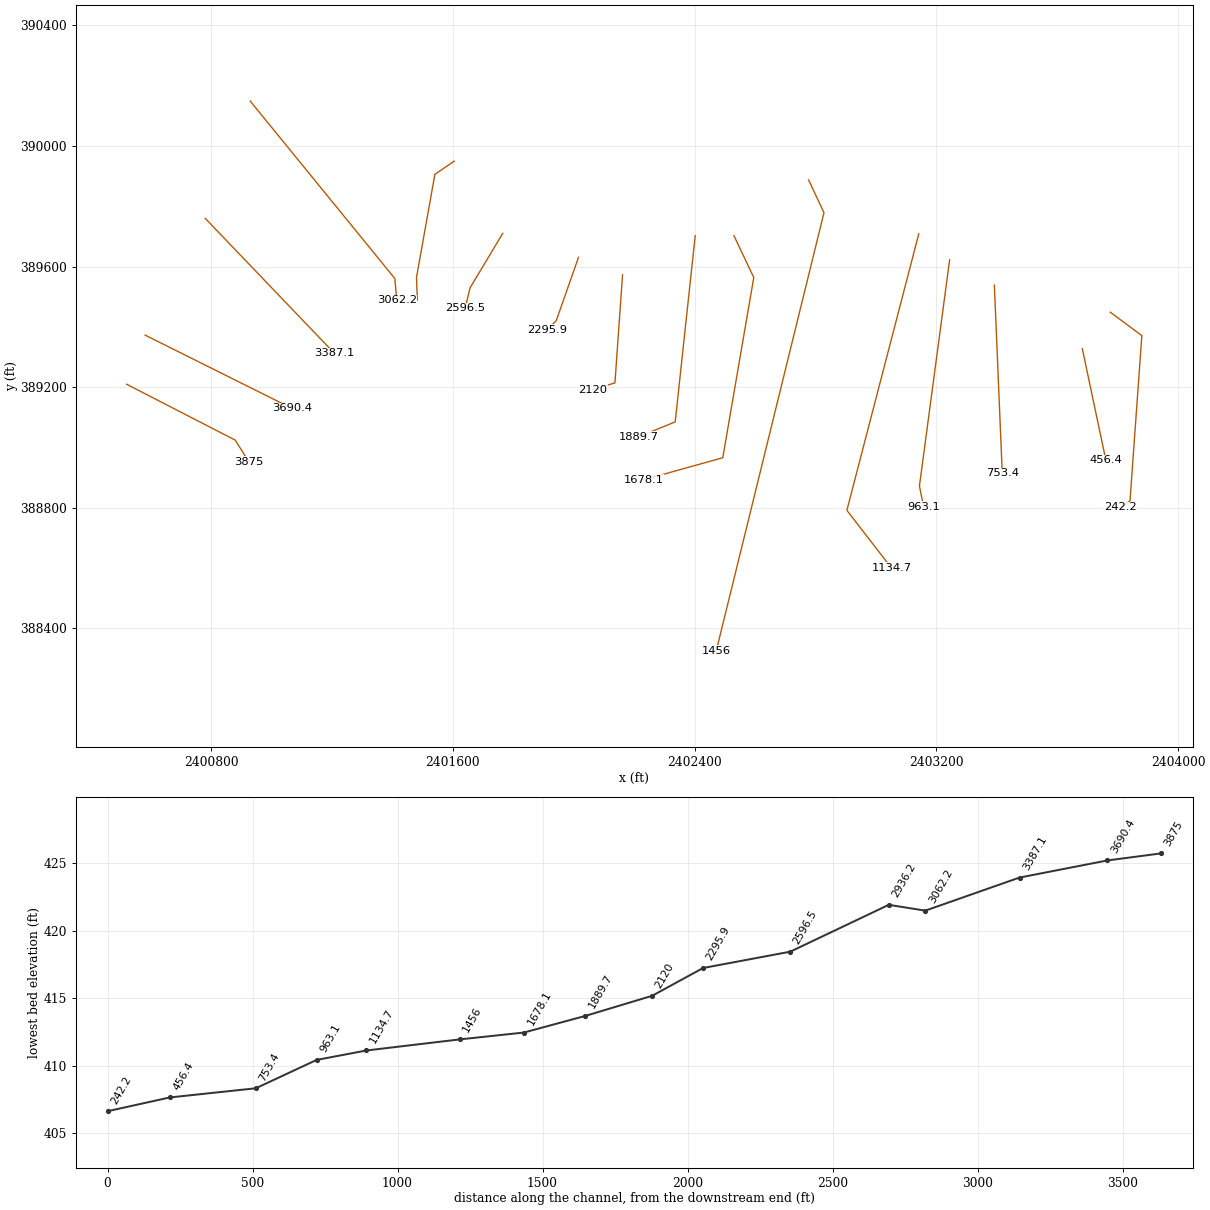
HEC-RAS study TULLISBRRN.prj: TULLISBRRN

--- TULLISBRRN.g01 (geometry) --- (continued)

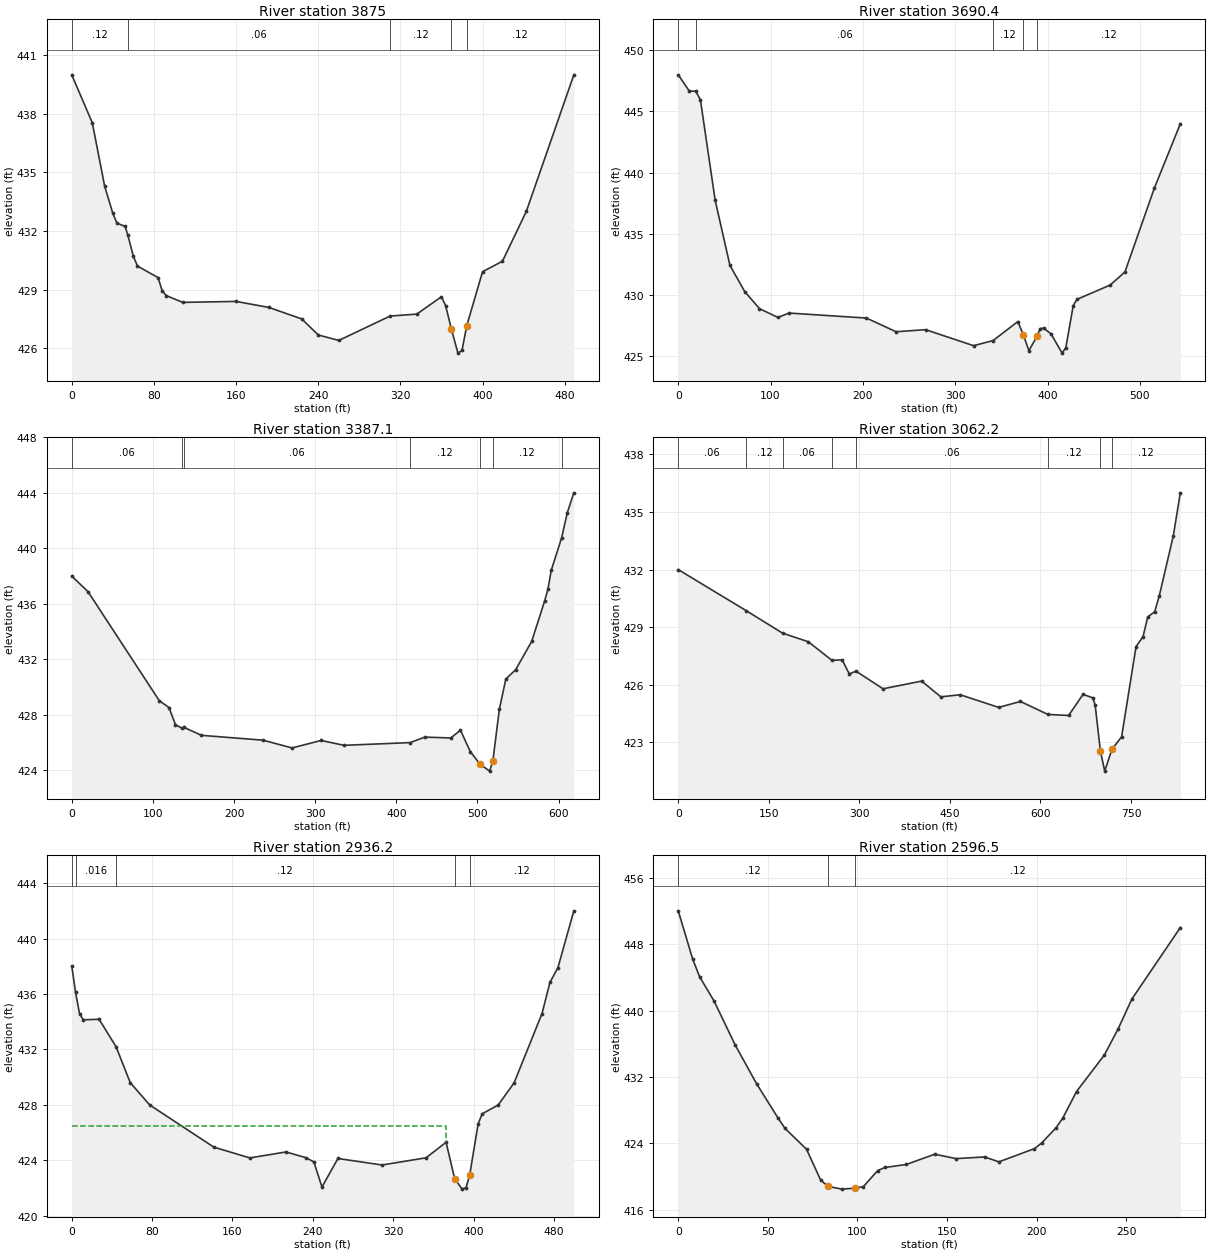
Type RM Length L Ch R = 1 ,3875    ,183.7,184.6,185.5
XS GIS Cut Line= 3
     2400521.143      389209.565     2400880.217      389024.434
     2400925.431      388952.537
#Sta/Elev= 30
       0     440      20  437.54      32   434.3      40   432.9      44   432.4
      52  432.23    54.6431.7815      60   430.7      64   430.2      84  429.61
      88  428.94      92  428.69     108  428.34     160  428.39     192  428.08
     224  427.49     240  426.67     260  426.39  309.98427.6399     336  427.74
     360  428.63     364  428.18   369.6  426.99     376  425.74     380  425.88
   384.6  427.14     400  429.91   419.4  430.45   442.6     433   488.9     440
#Mann= 5 ,-1 , 0
       0     .12       0    54.6     .06       0  309.98     .12       0
   369.6    .045       0   384.6     .12       0
Bank Sta=369.6,384.6
XS Rating Curve= 0 ,0
Exp/Cntr=0.3,0.1

Type RM Length L Ch R = 1 ,3690.4  ,311,303.3,295.5
XS GIS Cut Line= 2
     2400582.281      389372.537     2401068.661      389129.366
#Sta/Elev= 30
       0     448      12  446.67   18.94446.6537      24  445.97      40  437.73
      56   432.4      72  430.26      88  428.86     108  428.14     120   428.5
   203.9  428.09   235.9  426.97   267.9  427.14   319.9  425.83  341.01  426.25
   367.8   427.8   373.9   426.7   379.8  425.42   388.9  426.64   391.8  427.22
   395.8  427.27   403.8  426.79   415.8  425.22   419.8  425.67   427.8   429.1
   431.8  429.62   467.8  430.79   483.8  431.86   515.8  438.75   543.8  443.99
#Mann= 5 ,-1 , 0
       0     .12       0   18.94     .06       0  341.01     .12       0
   373.9    .045       0   388.9     .12       0
Bank Sta=373.9,388.9
XS Rating Curve= 0 ,0
Exp/Cntr=0.3,0.1

Type RM Length L Ch R = 1 ,3387.1  ,326.6,324.9,322.6
XS GIS Cut Line= 2
     2400781.182       389759.47      2401208.64      389312.012
#Sta/Elev= 30
       0     438      20  436.88   107.8  429.03   119.8  428.53   127.8   427.3
  136.11427.0323  138.38427.1004   159.7  426.53   235.6  426.18   271.5  425.62
   307.4  426.16   335.4  425.81  416.96 426.004   435.2   426.4   467.1  426.34
   479.1   426.9   491.1  425.36     503  424.46     515  423.95     519  424.69
     527  428.41     535  430.59     547  431.25   566.9   433.3   582.9  436.23
   586.9  437.06   590.9  438.41  603.59440.7273   610.8  442.58   618.8     444
#Mann= 7 ,-1 , 0
       0     .06       0  136.11     .08       0  138.38     .06       0
  416.96     .12       0     503    .045       0     519     .12       0
  603.59     .06       0
Bank Sta=503,519
XS Rating Curve= 0 ,0
Exp/Cntr=0.3,0.1

Type RM Length L Ch R = 1 ,3062.2  ,146.7,126,102.5
XS GIS Cut Line= 3
     2400929.896      390148.537     2401408.408      389560.243
      2401414.88      389487.303
#Sta/Elev= 30
       0     432  112.59429.8603  172.91428.6869   215.5  428.24  254.61427.2719
   271.4   427.3   283.4  426.56  294.39426.7101   339.2  425.79   403.1  426.19
     435  425.37     467  425.48   530.8  424.82   566.8  425.13  612.17424.4539
   646.6   424.4   670.5   425.5   686.5  425.32   690.5  424.96   699.2  422.56
   706.4   421.5   718.4  422.64   734.4  423.29   758.3  427.99   769.9  428.51
   777.6  429.53   789.2  429.81   796.9  430.65     820  433.76   831.6     436
#Mann= 8 ,-1 , 0
       0     .06       0  112.59     .12       0  172.91     .06       0
  254.61     .08       0  294.39     .06       0  612.17     .12       0
   699.2    .045       0   718.4     .12       0
Bank Sta=699.2,718.4
XS Rating Curve= 0 ,0
Exp/Cntr=0.3,0.1

Type RM Length L Ch R = 1 ,2936.2  ,348.5,339.6,329.5
XS GIS Cut Line= 4
     2401604.971      389949.394     2401540.928      389905.589
     2401480.114      389563.993     2401482.895      389488.743
#Sta/Elev= 30
       0  438.01    3.79 436.115     7.8  434.56    11.6  434.14    27.2  434.18
    44.1432.1995    58.2  429.61    77.6     428   141.4  424.96   177.3  424.18
   213.2  424.61   233.1   424.2   241.1  423.89   249.1  422.08     265  424.14
   308.9  423.67   352.8  424.19   372.7  425.31   381.2  422.68   388.7  421.93
   392.6  422.04   396.2  422.95   404.6  426.63   408.6  427.36   424.6     428
   440.4  429.59   468.2  434.59   476.1  436.84     484  437.89   499.9     442
#Mann= 5 ,-1 , 0
       0     .12       0    3.79    .016       0    44.1     .12       0
   381.2    .045       0   396.2     .12       0
#XS Ineff= 2 , 0
          372.24   426.5
Permanent Ineff=
       F       F
Bank Sta=381.2,396.2
XS Rating Curve= 0 ,0
Exp/Cntr=0.3,0.1

Type RM Length L Ch R = 1 ,2596.5  ,296.6,300.6,304.9
XS GIS Cut Line= 3
     2401765.441      389709.864      2401657.31       389529.07
     2401641.119      389461.542
#Sta/Elev= 30
       0  452.02       8  446.24    11.9  444.08    19.9  441.18    31.8  435.83
    43.7  431.17    55.6  427.06    59.6  425.78    71.6  423.26    79.5  419.53
    83.7  418.78    91.4  418.46    98.7  418.58   103.3  418.77   111.3   420.7
   115.3  421.07   127.2  421.43   143.1  422.67     155  422.14   170.9  422.34
   178.9  421.75   198.7  423.34   202.7  424.01   210.7  425.84   214.5  427.01
   222.2  430.23   237.7  434.62   245.4  437.78   253.1  441.39   280.1     450
#Mann= 3 ,-1 , 0
       0     .12       0    83.7    .045       0    98.7     .12       0
Bank Sta=83.7,98.7
XS Rating Curve= 0 ,0
Exp/Cntr=0.3,0.1

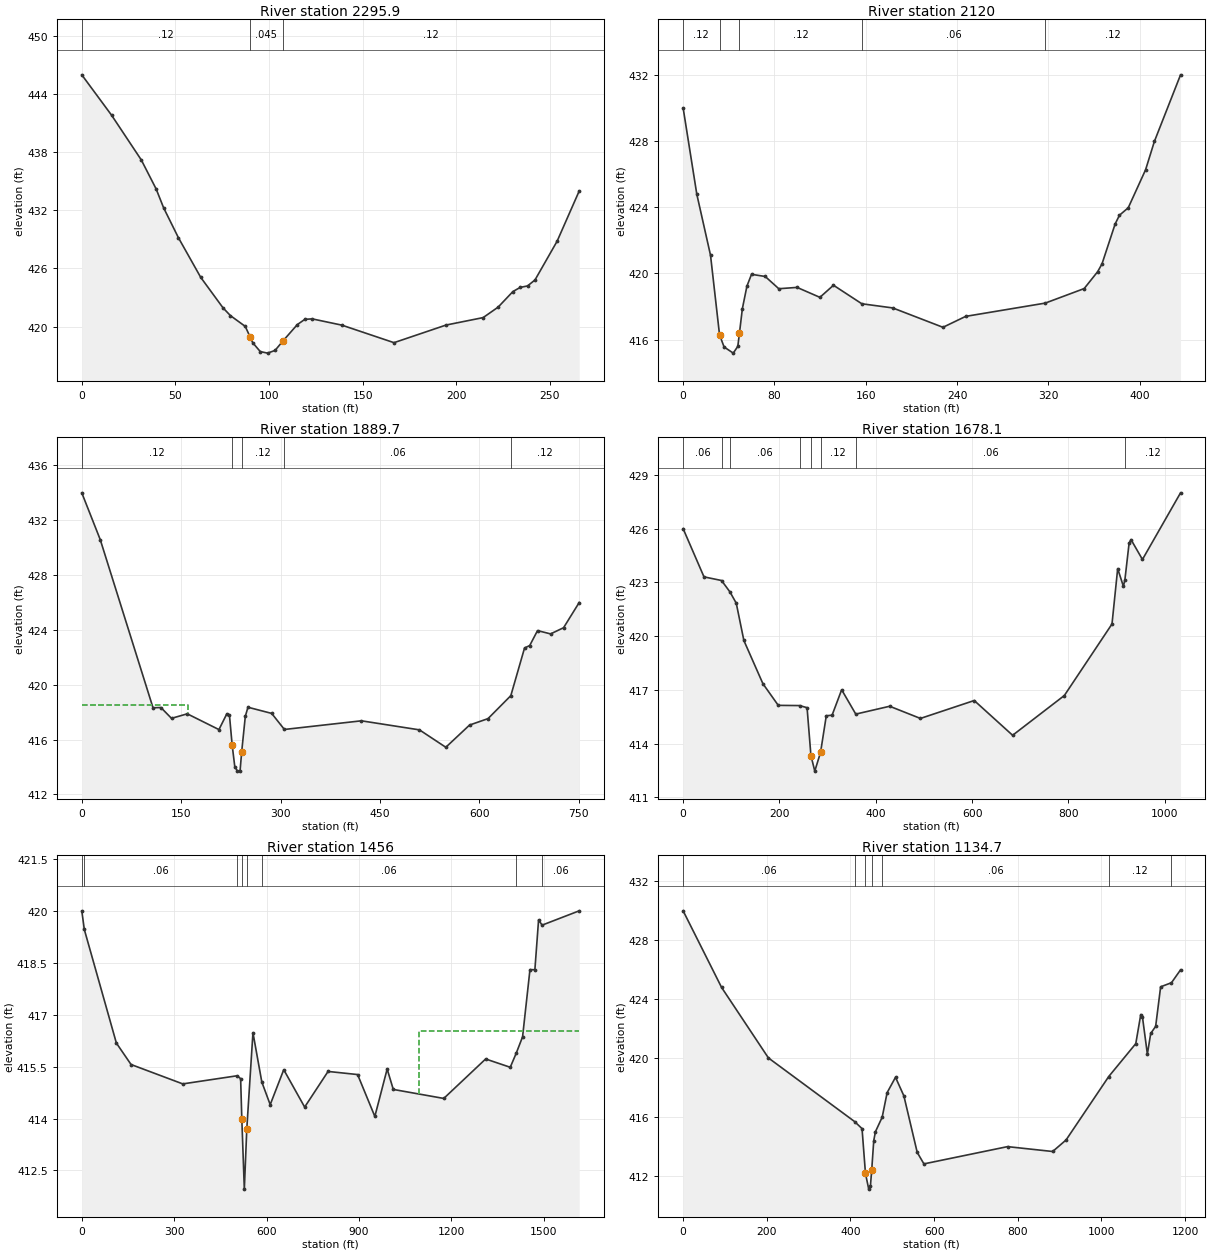
Type RM Length L Ch R = 1 ,2295.9  ,169.4,175.9,182.3
XS GIS Cut Line= 3
     2402016.114      389630.276     2401942.518      389420.537
     2401912.114      389389.733
#Sta/Elev= 30
       0     446    15.9  441.83    31.8   437.2    39.7  434.21    43.7  432.26
    51.6  429.17    63.5  425.08    75.4  421.93    79.4  421.12    87.3  420.01
    89.9  418.91    91.3  418.32    95.3  417.41    99.2  417.25   103.2  417.53
   107.2  418.46   115.1   420.2   119.1  420.74     123  420.79   138.9  420.14
   166.7  418.33   194.5  420.15   214.3  420.92   222.3     422   230.2  423.61
   234.1  424.04     238  424.19     242  424.81   253.8  428.81   265.6     434
#Mann= 3 ,-1 , 0
       0     .12       0    89.9    .045       0   107.2     .12       0
Bank Sta=89.9,107.2
XS Rating Curve= 0 ,0
Exp/Cntr=0.3,0.1

Type RM Length L Ch R = 1 ,2120    ,231.4,230.4,229.1
XS GIS Cut Line= 3
     2402161.932      389572.537     2402136.704      389214.127
     2402063.574      389191.997
#Sta/Elev= 30
       0     430      12  424.78      24   421.1    31.9  416.29    35.9  415.56
    43.9  415.19    47.9   415.6   49.37  416.42    51.9  417.88    55.9  419.24
    59.9  419.95    71.9  419.82    83.8  419.08    99.8  419.16   119.8  418.56
   131.7  419.29  156.54418.1711   183.6  417.92   227.6  416.75   247.5  417.41
  317.19418.2113   351.3  419.09   363.1  420.11   366.9  420.58   378.4  422.99
   382.2  423.52   389.9  423.97   405.1  426.27   412.8  427.98   435.7     432
#Mann= 5 ,-1 , 0
       0     .12       0    31.9    .045       0   49.37     .12       0
  156.54     .06       0  317.19     .12       0
Bank Sta=31.9,49.37
XS Rating Curve= 0 ,0
Exp/Cntr=0.3,0.1

Type RM Length L Ch R = 1 ,1889.7  ,213.5,211.6,208.8
XS GIS Cut Line= 3
     2402402.354      389702.297     2402336.114      389084.793
     2402216.114      389035.705
#Sta/Elev= 30
       0     434    27.9  430.58   107.5  418.32   119.4  418.34   135.4  417.55
   159.2  417.88     207  416.73     219  417.89   222.9  417.76   226.9  415.62
   230.9  414.03   234.9   413.7   238.9  413.73   241.3   415.1   246.8   417.7
   250.8  418.36   286.6  417.91  305.79416.7391     422  417.37   509.6  416.71
   549.4  415.44   585.2  417.06   613.1  417.53  647.49419.2046   668.2  422.68
     676  422.86   687.8  423.95   707.5  423.71   727.1  424.16   750.7     426
#Mann= 5 ,-1 , 0
       0     .12       0   226.9    .045       0   241.3     .12       0
  305.79     .06       0  647.49     .12       0
#XS Ineff= 2 , 0
          160.99  418.49
Permanent Ineff=
       F       F
Bank Sta=226.9,241.3
XS Rating Curve= 0 ,0
Exp/Cntr=0.3,0.1

Type RM Length L Ch R = 1 ,1678.1  ,215,222,220.3
XS GIS Cut Line= 4
     2402530.403      389702.248     2402596.114      389563.353
     2402493.516      388965.938     2402230.814      388892.537
#Sta/Elev= 30
       0     426    43.3  423.31   79.75423.1075   97.36422.4634   110.3  421.84
   126.1  419.76   165.6  417.35   197.5  416.14  241.67 416.128   257.3  416.01
   265.3  413.34   273.3  412.47   285.3  413.52   297.2  415.56   309.2  415.59
   329.1  417.01  358.39415.6522   428.8  416.09   492.6  415.41   604.3  416.41
     684  414.47   791.4  416.69   890.3  420.68   902.1  423.77     914  422.78
  917.14423.1584   925.8  425.19   929.8  425.39   953.5  424.28  1032.6     428
#Mann= 8 ,-1 , 0
       0     .06       0   79.75     .12       0   97.36     .06       0
  241.67     .12       0   265.3    .045       0   285.3     .12       0
  358.39     .06       0  917.14     .12       0
Bank Sta=265.3,285.3
XS Rating Curve= 0 ,0
Exp/Cntr=0.3,0.1

Type RM Length L Ch R = 1 ,1456    ,321.7,321.3,321
XS GIS Cut Line= 3
     2402777.495      389887.156     2402828.361      389778.415
     2402472.114      388326.325
#Sta/Elev= 30
       0     420     8.2419.4611   112.3  416.18     160  415.56   327.9     415
  504.84415.2356   515.8  415.15   519.6     414   527.8  411.96   535.8   413.7
   555.8  416.48   584.6 415.054   611.8   414.4   655.8  415.41   723.7  414.33
   799.7  415.36   895.6  415.27   951.6  414.06   991.6  415.43  1011.5  414.84
  1175.4  414.58  1311.4  415.72  1391.3  415.48 1410.97415.8926  1431.3  416.36
  1455.3   418.3  1471.3   418.3  1483.3  419.74 1494.67419.5863  1615.2     420
#Mann= 8 ,-1 , 0
       0     .12       0     8.2     .06       0  504.84     .12       0
   519.6    .045       0   535.8     .12       0   584.6     .06       0
 1410.97     .12       0 1494.67     .06       0
#XS Ineff= 2 , 0
                         1094.12          416.54
Permanent Ineff=
       F       F
Bank Sta=519.6,535.8
XS Rating Curve= 0 ,0
Exp/Cntr=0.3,0.1

Type RM Length L Ch R = 1 ,1134.7  ,169.5,171.6,173.7
XS GIS Cut Line= 3
     2403142.146      389708.537     2402904.114      388791.524
      2403051.84      388600.263
#Sta/Elev= 30
       0     430    91.9  424.81   203.9  420.03  409.84415.7205   427.7  415.24
   435.9   412.2   443.7  411.14   447.7  411.33   450.9  412.47   455.7  414.43
   459.7  415.03  475.85 416.014   487.7  417.68   507.7  418.72   527.7  417.46
   559.6  413.63   575.6  412.85   775.5  414.02   883.4  413.69   915.4  414.47
 1017.48418.7718  1082.1     421    1094  422.97    1098  422.82  1109.8  420.29
  1117.8  421.69  1129.6  422.17  1141.5  424.85 1167.46425.1292  1189.1     426
#Mann= 7 ,-1 , 0
       0     .06       0  409.84     .12       0   435.9    .045       0
   450.9     .12       0  475.85     .06       0 1017.48     .12       0
 1167.46     .06       0
Bank Sta=435.9,450.9
XS Rating Curve= 0 ,0
Exp/Cntr=0.3,0.1

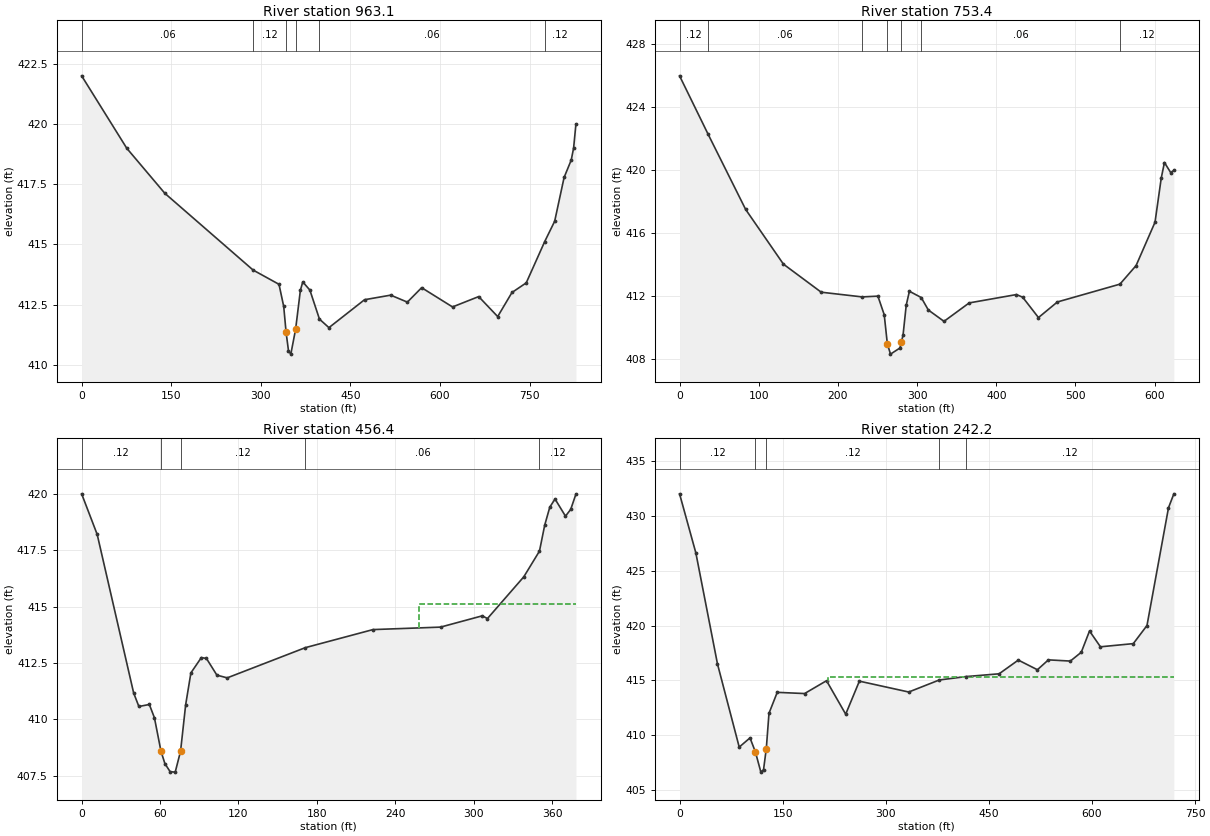
Type RM Length L Ch R = 1 ,963.1   ,205.1,209.7,214.4
XS GIS Cut Line= 3
     2403244.114       389622.04     2403144.234      388872.417
     2403158.064      388802.487
#Sta/Elev= 30
       0     422    75.6  418.99   139.3  417.12  287.01413.9328   330.4  413.34
   338.3  412.42   342.3  411.34   346.3  410.58   350.2  410.44   358.2  411.47
   366.2  413.09   370.2  413.44   382.1   413.1  398.13411.8945     414  411.54
   473.6   412.7   517.4  412.89   545.3   412.6   569.2   413.2   620.9   412.4
   664.7  412.83   696.5     412   720.4     413   744.3   413.4  775.26415.1177
   791.9  415.96   807.7  417.78   819.6   418.5   823.6     419   827.5     420
#Mann= 6 ,-1 , 0
       0     .06       0  287.01     .12       0   342.3    .045       0
   358.2     .12       0  398.13     .06       0  775.26     .12       0
Bank Sta=342.3,358.2
XS Rating Curve= 0 ,0
Exp/Cntr=0.3,0.1

Type RM Length L Ch R = 1 ,753.4   ,292.8,297,300.4
XS GIS Cut Line= 2
     2403392.114      389538.452     2403418.262      388914.685
#Sta/Elev= 30
       0     426   36.12422.2884    83.5  417.52   131.2  414.05   178.9  412.27
  230.56411.9712   250.5  412.02   258.5  410.84   262.4  409.01   266.4  408.34
   278.4  408.73   280.3  409.13   282.3  409.56   286.3  411.45   290.3  412.33
  305.24411.9312   314.2  411.14     334  410.42   365.8  411.59   425.5  412.12
   433.4  411.95   453.3  410.66   477.2  411.65  556.17412.7801   576.6  413.96
   600.5  416.71   608.4  419.52   612.4   420.5   620.3  419.86   624.3     420
#Mann= 7 ,-1 , 0
       0     .12       0   36.12     .06       0  230.56     .12       0
   262.4    .045       0   280.3     .12       0  305.24     .06       0
  556.17     .12       0
Bank Sta=262.4,280.3
XS Rating Curve= 0 ,0
Exp/Cntr=0.3,0.1

Type RM Length L Ch R = 1 ,456.4   ,197.7,214.2,212.9
XS GIS Cut Line= 2
     2403683.168      389327.591     2403761.149      388957.572
#Sta/Elev= 30
       0     420    11.9   418.2    39.8  411.17    43.8  410.57    51.8  410.66
    55.7  410.07    60.7  408.59    63.7  408.04    67.7  407.68    71.6  407.66
    75.7  408.59    79.6  410.65    83.6  412.06    91.6  412.74    95.5   412.7
   103.5  411.96   111.4  411.84   171.2  413.18   222.9  413.98   274.6  414.09
   306.5  414.59   310.5  414.47   338.3  416.32   350.3  417.46   354.3  418.61
   358.2  419.41   362.2  419.77   370.2  419.01   374.2  419.31   378.2  419.99
#Mann= 5 ,-1 , 0
       0     .12       0    60.7    .045       0    75.7     .12       0
   171.2     .06       0   350.3     .12       0
#XS Ineff= 2 , 0
                          258.41           415.1
Permanent Ineff=
       F       F
Bank Sta=60.7,75.7
XS Rating Curve= 0 ,0
Exp/Cntr=0.3,0.1

Type RM Length L Ch R = 1 ,242.2   ,257.5,242.2,244.8
XS GIS Cut Line= 4
     2403775.691      389448.537     2403880.114      389370.904
     2403840.888       388822.37     2403808.131      388801.058
#Sta/Elev= 30
       0     432    23.7  426.62    55.2  416.49    86.8  408.92   102.5  409.76
   110.4  408.47   118.3  406.64   122.2  406.87   126.2  408.79   130.1     412
   142.1  413.91   181.9   413.8   213.8  414.97   241.7  411.92   261.6  414.93
   333.4  413.94  377.82415.0362  416.63415.3462   464.9   415.6   492.8  416.85
   520.6  415.97   536.6  416.87   568.5  416.76   584.4  417.56   596.4   419.5
   612.3  418.06   660.1  418.35     680     420   711.3  430.73   719.1     432
#Mann= 5 ,-1 , 0
       0     .12       0   110.4    .045       0   126.2     .12       0
  377.82     .06       0  416.63     .12       0
#XS Ineff= 2 , 0
                          215.48          415.34
Permanent Ineff=
       F       F
Bank Sta=110.4,126.2
XS Rating Curve= 0 ,0
Exp/Cntr=0.3,0.1
LCMann Table=0

Chan Stop Cuts=-1
Use User Specified Reach Order=0
Composite Channel Slope=5